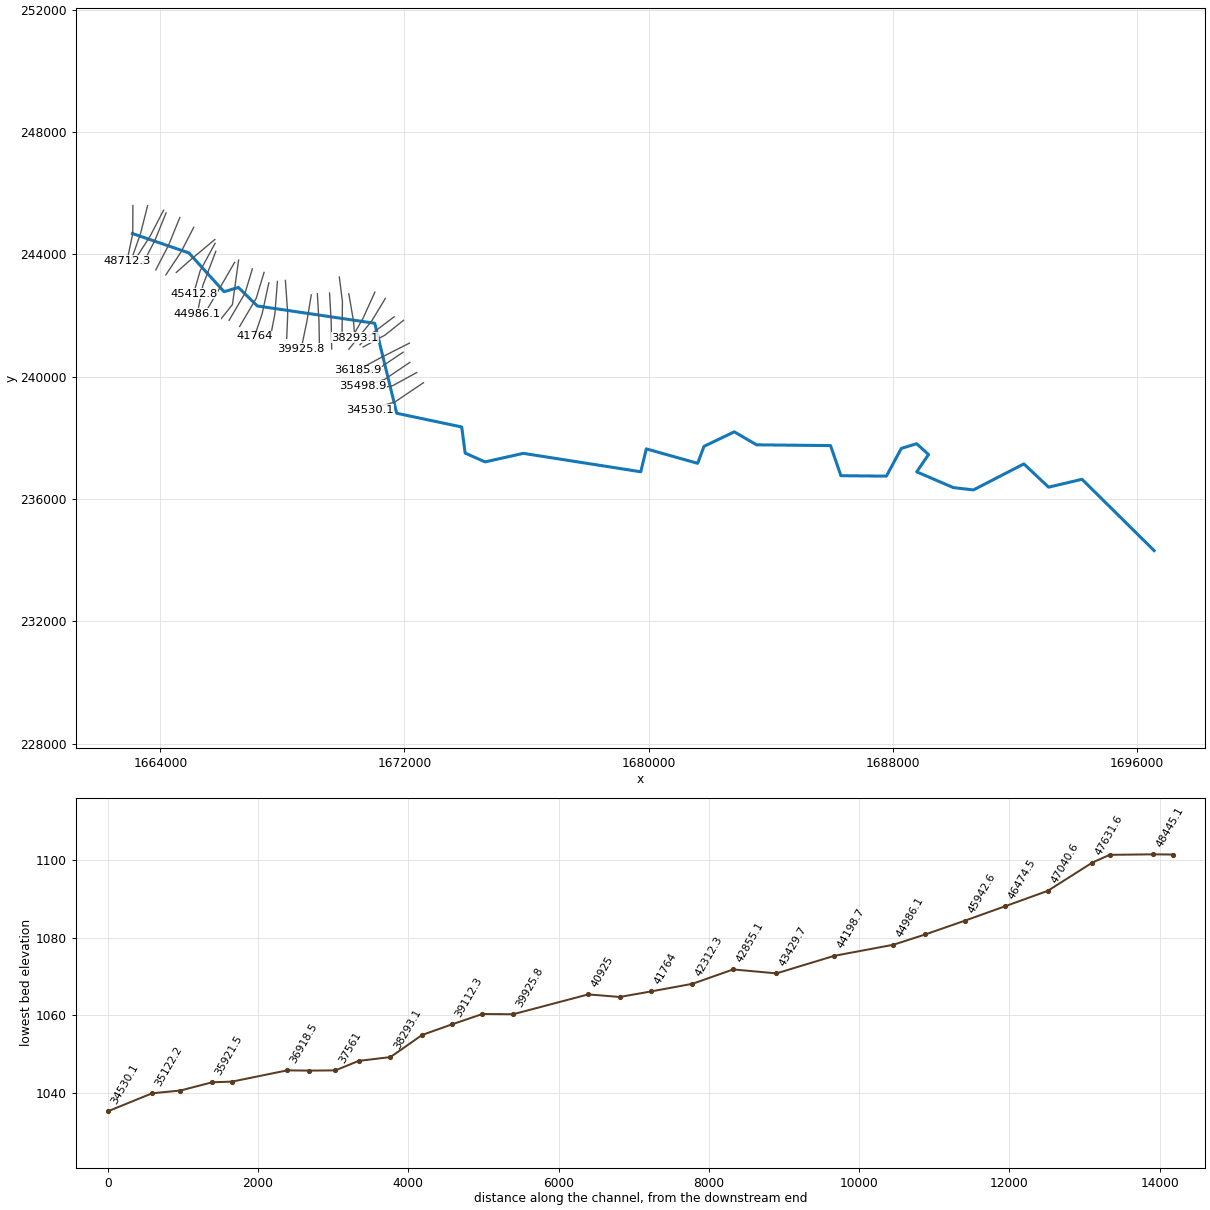
--- KinchloCr.prj (project) ---

Proj Title=KinchloCr
Current Plan=p01
Geom File=g01
Flow File=f01
Plan File=p01
DSS Export Rating Curves=0
DSS Export Rating Curve Sorted=0
DSS Export Volume Flow Curves=0
DXF OffsetX=0
DXF OffsetY=0
DXF ScaleX=0
DXF ScaleY=0

--- KinchloCr.p01 (plan) ---

Plan Title=Floodplain
Program Version=4.00
Geom File=g01
Flow File=f01
K Sum by GR=0
Std Step Tol=0.01
Critical Tol=0.01
Num of Std Step Trials=20
Max Error Tol=0.3
Flow Tol Ratio=0.001
Split Flow NTrial=30
Split Flow Tol=0.02
Split Flow Ratio=0.02
Log Output Level=0
Friction Slope Method=1
Unsteady Friction Slope Method=2
Unsteady Bridges Friction Slope Method=1
Global Log Level=0
CheckData=False
Run HTab=0
Run UNet=0
Run PostProcess=0
UNET Theta=0
UNET Theta Warmup=0
UNET ZTol=0
UNET ZSATol=0
UNET MxIter=0
UNET MaxInSteps=0
UNET DtIC=0
UNET DtMin=0
UNET MaxCRTS=0
UNET WFStab=0
UNET SFStab=0
UNET WFX=0
UNET SFX=0
UNET DSS MLevel=0
UNET DZMax Abort=0
UNET Convert EG Bridges=0
UNET Use Existing IB Tables=0
UNET Froude Limit=0
UNET Froude Power=0
Write IC File=0
Echo Input=False
Echo Output=False
Write Detailed=0

--- KinchloCr.f01 (steady flow) ---

Flow Title=NFF Regression Equation
Program Version=4.00
Number of Profiles=1
Profile Names=P100yr
River Rch & RM=KinchloCr,Main      ,48712.3
764.0547
River Rch & RM=KinchloCr,Main      ,45412.8
862.8900
River Rch & RM=KinchloCr,Main      ,44986.1
943.8470
River Rch & RM=KinchloCr,Main      ,43429.7
965.1096
River Rch & RM=KinchloCr,Main      ,38293.1
1070.265
River Rch & RM=KinchloCr,Main      ,37870.8
1575.577
River Rch & RM=KinchloCr,Main      ,36185.9
1710.060
River Rch & RM=KinchloCr,Main      ,35921.5
2224.812
River Rch & RM=KinchloCr,Main      ,32901.6
2266.281
River Rch & RM=KinchloCr,Main      ,24413
2517.838
River Rch & RM=KinchloCr,Main      ,23980.5
2844.988
River Rch & RM=KinchloCr,Main      ,18202.7
2960.968
River Rch & RM=KinchloCr,Main      ,17986.4
3749.261
River Rch & RM=KinchloCr,Main      ,9471.1
4006.193
River Rch & RM=KinchloCr,Main      ,9287.7
4008.852
River Rch & RM=KinchloCr,Main      ,9124.7
4008.852
River Rch & RM=KinchloCr,Main      ,373.7
4291.762
Boundary for River Rch & Prof#=KinchloCr,Main      ,1
Up Type=0
Dn Type=3
Dn Slope=0.001033

--- KinchloCr.g01 (geometry) ---

Geom Title=USGS 3m DEM
Program Version=4.00

River Reach=KinchloCr     ,Main
Reach XY= 30
     1663084.663      244678.738     1664932.830      244046.645
     1666087.258      242777.901     1666556.895      242917.066
     1667178.113      242311.861     1671026.145      241745.439
     1671745.766      238804.113     1673876.979      238355.979
     1673987.850      237503.315     1674642.499      237214.249
     1675894.714      237493.599     1679744.692      236891.222
     1679926.362      237639.624     1681608.992      237167.857
     1681817.421      237722.556     1682809.049      238196.898
     1683539.070      237772.503     1685964.836      237747.359
     1686303.677      236763.164     1687794.339      236748.796
     1688283.585      237654.567     1688785.112      237808.689
     1689176.623      237456.204     1688789.310      236888.882
     1689990.220      236374.035     1690647.292      236298.116
     1692300.255      237148.138     1693110.900      236387.998
     1694205.741      236645.658     1696567.484      234316.444

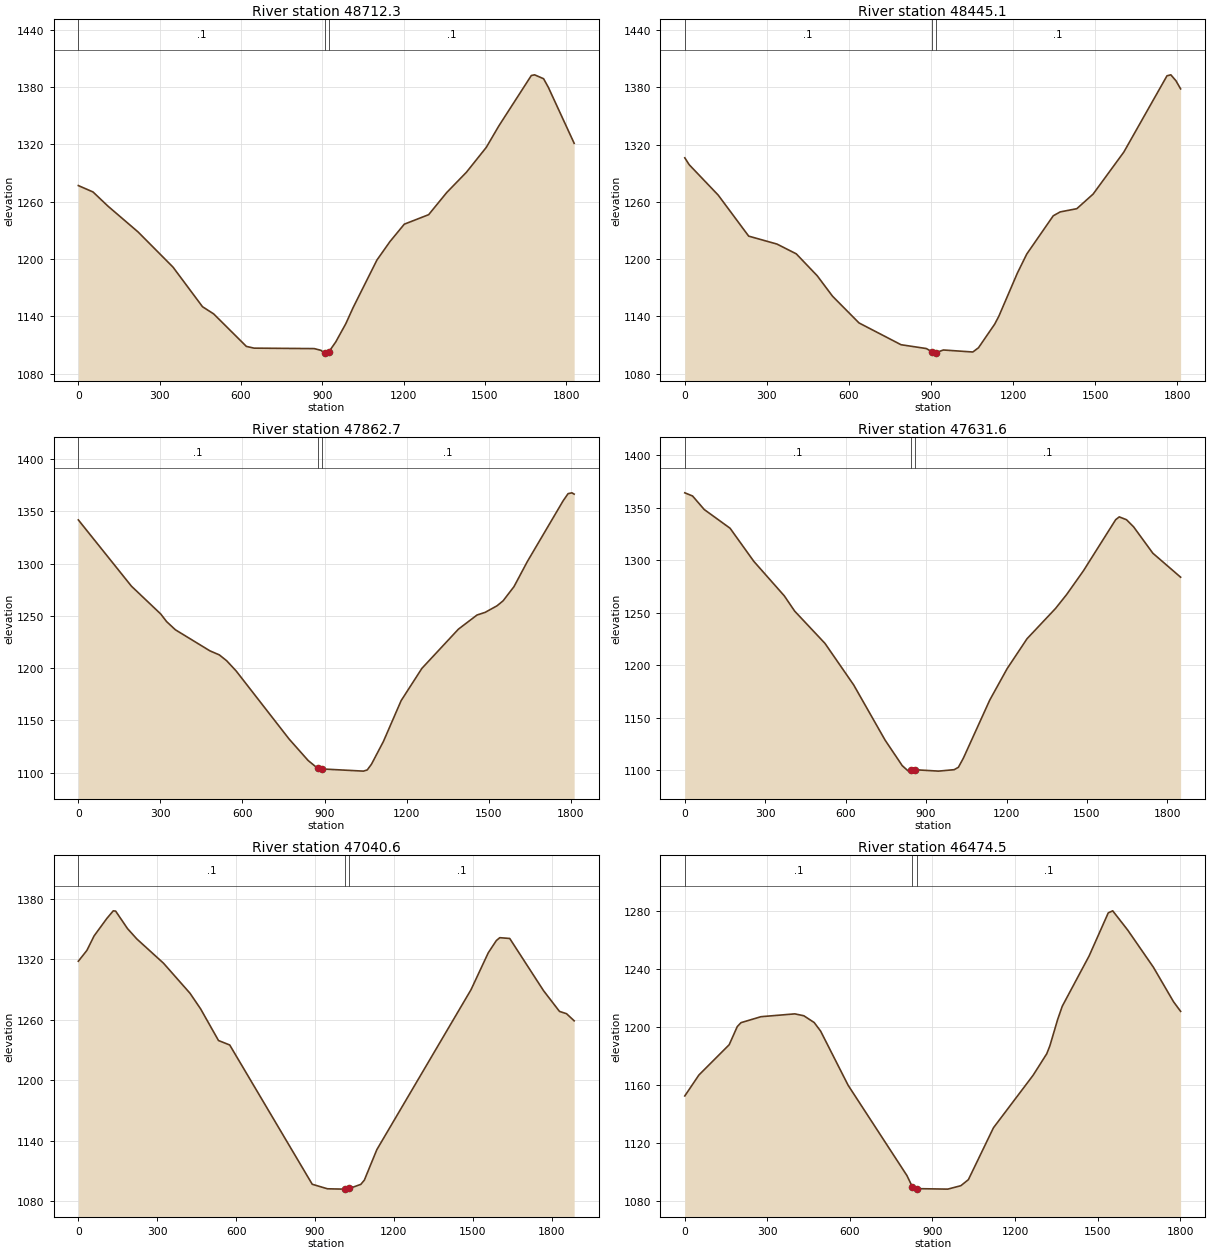
Type RM Length L Ch R = 1 ,48712.3,272.775,267.194,266.165
XS GIS Cut Line= 3
     1663099.816      245594.634     1663094.586      244677.497
     1662906.837      243784.596
#Sta/Elev= 30
       0 1276.75    54.1 1270.08   109.6 1255.17   220.5 1228.21   349.4 1191.43
   458.2 1150.01   499.3 1142.52   620.1 1108.49   648.4 1106.67   870.6 1106.19
   895.5 1104.36   907.4 1101.46   909.7 1101.51   924.7 1102.93   949.6 1113.03
   986.9 1132.19  1013.7 1148.93  1101.8 1198.82  1149.8 1218.12  1202.8 1236.36
  1292.7 1246.30  1359.3 1269.45  1432.1 1290.70  1505.2 1316.66  1551.7 1339.16
  1671.5 1391.87  1683.6 1392.61  1716.8 1388.53  1734.1 1379.68  1829.6 1321.00
#Mann= 3 , 0 , 0
       0     0.1       0   909.7   0.045       0   924.7     0.1       0
Bank Sta=   909.7,   924.7
Exp/Cntr=0.3,0.1

Type RM Length L Ch R = 1 ,48445.1,591.892,582.413,540.112
XS GIS Cut Line= 3
     1663581.109      245590.360     1663346.499      244666.305
     1663059.460      243856.737
#Sta/Elev= 30
       0 1306.07    16.2 1298.83   122.1 1267.03   233.5 1224.06   336.9 1215.74
   407.5 1205.50   484.4 1182.42   540.1 1161.09   636.8 1133.13   790.4 1110.31
   882.7 1106.32   901.8 1103.19   914.0 1101.51   916.8 1101.85   945.1 1104.79
  1052.8 1102.69  1073.5 1107.15  1132.7 1131.88  1147.6 1139.99  1215.8 1185.46
  1250.0 1205.32  1346.8 1245.38  1372.0 1249.41  1432.9 1252.80  1492.4 1268.08
  1604.7 1312.10  1762.5 1392.00  1776.5 1393.01  1795.1 1386.85  1812.3 1378.28
#Mann= 3 , 0 , 0
       0     0.1       0   901.8   0.045       0   916.8     0.1       0
Bank Sta=   901.8,   916.8
Exp/Cntr=0.3,0.1

Type RM Length L Ch R = 1 ,47862.7,226.708,231.031,233.939
XS GIS Cut Line= 3
     1664104.906      245441.216     1663664.917      244595.445
     1663200.110      243873.124
#Sta/Elev= 30
       0 1341.95   194.1 1278.48   301.2 1251.84   322.7 1244.54   354.7 1236.74
   481.2 1216.52   515.3 1212.70   542.1 1207.10   576.6 1197.37   770.6 1132.05
   840.0 1111.55   875.4 1103.95   890.4 1103.46  1042.0 1101.38  1056.0 1102.51
  1071.4 1107.96  1115.1 1129.78  1179.9 1168.88  1255.8 1199.78  1389.3 1237.33
  1457.1 1250.84  1487.3 1253.45  1530.3 1259.68  1552.7 1264.49  1592.5 1278.09
  1641.2 1302.07  1772.4 1360.40  1790.1 1367.07  1804.2 1367.87  1812.3 1366.62
#Mann= 3 , 0 , 0
       0     0.1       0   875.4   0.045       0   890.4     0.1       0
Bank Sta=   875.4,   890.4
Exp/Cntr=0.3,0.1

Type RM Length L Ch R = 1 ,47631.6,579.056,591.011,590.164
XS GIS Cut Line= 3
     1664187.566      245355.217     1663820.528      244455.392
     1663415.847      243676.914
#Sta/Elev= 30
       0 1364.27    29.0 1361.24    72.6 1348.36   168.9 1330.55   257.3 1299.08
   371.2 1266.16   410.0 1251.60   522.7 1220.99   629.8 1181.43   747.2 1128.80
   811.1 1104.53   832.2 1099.72   844.4 1100.20   859.4 1100.68   946.4 1099.36
  1004.6 1100.74  1020.4 1103.01  1039.4 1111.94  1137.2 1166.93  1202.2 1196.92
  1276.4 1225.39  1382.8 1254.23  1424.2 1267.50  1486.6 1290.01  1607.0 1338.70
  1620.4 1341.38  1647.5 1338.64  1673.9 1331.87  1745.6 1306.79  1849.2 1283.96
#Mann= 3 , 0 , 0
       0     0.1       0   844.4   0.045       0   859.4     0.1       0
Bank Sta=   844.4,   859.4
Exp/Cntr=0.3,0.1

Type RM Length L Ch R = 1 ,47040.6,567.676,566.102,532.976
XS GIS Cut Line= 3
     1664637.981      245204.142     1664263.981      244287.250
     1663850.799      243492.418
#Sta/Elev= 30
       0 1318.21    32.5 1328.92    60.0 1343.34   108.4 1360.63   132.9 1368.22
   142.0 1367.93   187.2 1350.54   222.3 1340.36   324.2 1316.19   425.0 1286.36
   465.1 1270.95   533.2 1239.52   575.8 1235.12   889.7 1096.92   947.5 1092.43
  1006.6 1092.09  1015.9 1092.24  1030.9 1092.72  1074.6 1096.83  1088.0 1101.06
  1135.4 1131.24  1493.6 1289.92  1559.3 1326.58  1590.0 1338.71  1603.1 1341.57
  1640.9 1340.80  1769.7 1288.94  1830.2 1268.44  1857.0 1266.14  1886.0 1259.10
#Mann= 3 , 0 , 0
       0     0.1       0  1015.9   0.045       0  1030.9     0.1       0
Bank Sta=  1015.9,  1030.9
Exp/Cntr=0.3,0.1

Type RM Length L Ch R = 1 ,46474.5,539.645,531.892,522.878
XS GIS Cut Line= 3
     1665092.561      244880.710     1664678.118      244077.768
     1664180.043      243330.083
#Sta/Elev= 30
       0 1152.44    51.3 1166.89   161.3 1187.78   190.7 1200.30   204.3 1203.02
   276.8 1207.13   399.8 1209.09   432.6 1207.78   470.3 1203.11   493.5 1197.24
   593.6 1159.81   807.5 1097.43   827.1 1089.67   842.1 1088.46   955.8 1088.12
  1003.4 1090.50  1030.7 1094.67  1121.7 1130.45  1266.0 1166.74  1315.4 1181.54
  1326.8 1187.04  1355.3 1205.34  1371.8 1214.35  1469.6 1249.13  1539.1 1278.83
  1555.2 1280.21  1609.4 1267.01  1702.8 1241.36  1776.4 1217.40  1802.0 1210.83
#Mann= 3 , 0 , 0
       0     0.1       0   827.1   0.045       0   842.1     0.1       0
Bank Sta=   827.1,   842.1
Exp/Cntr=0.3,0.1

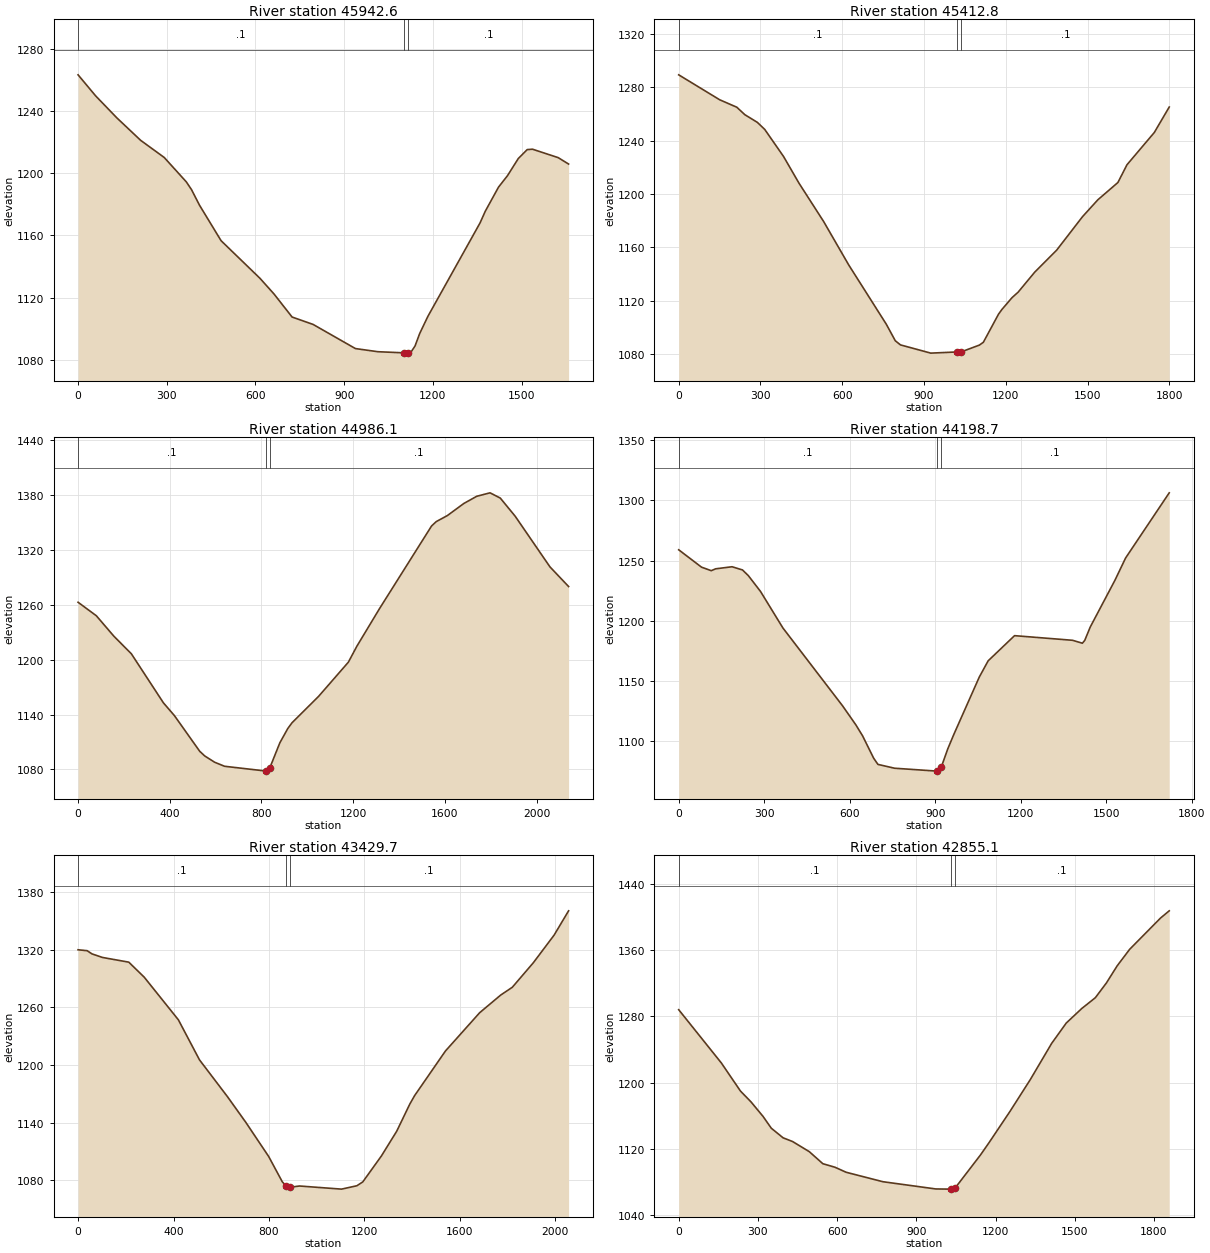
Type RM Length L Ch R = 1 ,45942.6,519.884,529.81,543.229
XS GIS Cut Line= 3
     1665783.778      244483.425     1664975.675      243808.855
     1664520.904      243407.314
#Sta/Elev= 30
       0 1263.18    59.4 1249.67   131.2 1235.53   211.8 1221.09   291.4 1210.10
   366.1 1194.43   383.7 1189.46   410.8 1179.43   483.8 1156.63   615.1 1132.52
   662.6 1122.46   724.0 1107.60   795.0 1102.86   938.2 1087.35  1014.0 1085.33
  1101.7 1084.61  1116.7 1084.49  1123.8 1084.42  1139.8 1088.98  1155.6 1097.00
  1183.3 1108.02  1359.8 1168.06  1377.3 1175.49  1422.2 1191.02  1452.8 1198.45
  1489.1 1209.40  1519.3 1215.15  1537.2 1215.41  1624.1 1209.99  1659.3 1205.87
#Mann= 3 , 0 , 0
       0     0.1       0  1101.7   0.045       0  1116.7     0.1       0
Bank Sta=  1101.7,  1116.7
Exp/Cntr=0.3,0.1

Type RM Length L Ch R = 1 ,45412.8,419.696,426.74,312.132
XS GIS Cut Line= 3
     1665792.672      244358.916     1665303.531      243460.674
     1665090.087      242713.622
#Sta/Elev= 30
       0 1289.33   150.3 1270.65   213.2 1265.06   242.7 1259.46   288.5 1253.72
   315.6 1248.45   384.8 1228.12   441.0 1208.26   531.9 1179.39   623.7 1146.93
   761.7 1102.49   794.6 1090.12   813.7 1087.01   924.8 1080.85  1021.8 1081.74
  1036.8 1081.82  1103.0 1086.86  1117.7 1088.97  1173.5 1110.08  1185.9 1113.57
  1222.6 1122.34  1245.4 1126.54  1306.2 1141.51  1386.8 1158.01  1481.5 1183.06
  1537.8 1195.71  1611.4 1208.67  1644.7 1221.97  1744.9 1246.12  1799.7 1265.20
#Mann= 3 , 0 , 0
       0     0.1       0  1021.8   0.045       0  1036.8     0.1       0
Bank Sta=  1021.8,  1036.8
Exp/Cntr=0.3,0.1

Type RM Length L Ch R = 1 ,44986.1,786.597,787.374,727.4
XS GIS Cut Line= 3
     1665816.678      244097.065     1665392.727      242986.169
     1665209.677      242053.169
#Sta/Elev= 30
       0 1262.80    79.9 1248.00   156.2 1225.69   232.4 1206.49   372.2 1152.88
   420.4 1138.84   530.6 1099.89   552.8 1094.72   595.5 1087.93   639.1 1083.47
   821.5 1078.21   824.3 1078.17   836.5 1081.76   880.1 1109.05   914.7 1124.70
   933.3 1131.03  1049.2 1159.89  1179.1 1197.28  1216.1 1214.68  1315.6 1256.08
  1542.2 1346.24  1562.6 1350.98  1610.9 1357.56  1682.9 1370.81  1739.1 1378.66
  1797.1 1382.44  1841.9 1376.68  1907.1 1356.76  2058.5 1301.48  2139.8 1280.00
#Mann= 3 , 0 , 0
       0     0.1       0   821.5   0.045       0   836.5     0.1       0
Bank Sta=   821.5,   836.5
Exp/Cntr=0.3,0.1

Type RM Length L Ch R = 1 ,44198.7,730.917,769.069,776.068
XS GIS Cut Line= 3
     1666433.003      243736.372     1666035.511      243050.250
     1665564.564      242250.221
#Sta/Elev= 30
       0 1259.07    80.1 1244.63   114.3 1241.72   129.7 1243.27   187.2 1244.99
   223.8 1242.34   244.3 1237.62   286.9 1224.55   365.8 1194.11   574.7 1129.61
   621.7 1113.70   645.3 1104.58   684.0 1086.08   699.1 1080.90   757.4 1077.72
   906.1 1075.32   906.7 1075.31   921.1 1078.46   944.3 1093.86   965.8 1105.98
  1054.9 1153.47  1085.9 1166.89  1178.5 1187.78  1382.2 1183.93  1416.5 1181.50
  1424.8 1183.85  1444.1 1194.94  1531.0 1233.87  1568.3 1252.30  1721.3 1306.36
#Mann= 3 , 0 , 0
       0     0.1       0   906.1   0.045       0   921.1     0.1       0
Bank Sta=   906.1,   921.1
Exp/Cntr=0.3,0.1

Type RM Length L Ch R = 1 ,43429.7,582.68,574.548,566.509
XS GIS Cut Line= 3
     1666564.099      243811.827     1666361.855      242357.883
     1665994.711      241899.150
#Sta/Elev= 30
       0 1319.77    37.9 1318.82    58.4 1315.49   102.2 1311.79   212.6 1306.88
   277.1 1291.30   420.4 1246.89   508.9 1205.23   626.4 1166.84   703.8 1139.95
   798.7 1104.74   856.0 1078.30   872.5 1074.02   879.9 1072.06   887.5 1072.71
   927.7 1074.03  1104.0 1070.78  1168.3 1074.29  1193.2 1078.33  1271.2 1105.31
  1335.4 1131.08  1389.7 1159.04  1410.2 1168.03  1539.4 1214.46  1683.0 1254.34
  1771.3 1272.71  1819.7 1280.78  1908.1 1306.39  1994.8 1335.03  2055.5 1360.29
#Mann= 3 , 0 , 0
       0     0.1       0   872.5   0.045       0   887.5     0.1       0
Bank Sta=   872.5,   887.5
Exp/Cntr=0.3,0.1

Type RM Length L Ch R = 1 ,42855.1,535.982,542.816,538.729
XS GIS Cut Line= 3
     1667015.419      243524.660     1666773.354      242726.677
     1666253.983      241844.387
#Sta/Elev= 30
       0 1288.17   161.7 1223.85   233.9 1190.07   273.9 1176.98   319.3 1159.52
   350.6 1145.27   395.3 1133.68   431.3 1129.19   494.5 1117.00   545.8 1102.47
   592.1 1098.16   634.1 1092.13   773.4 1080.73   973.5 1072.01  1030.8 1071.80
  1031.9 1071.85  1046.9 1073.17  1142.8 1112.98  1175.1 1127.76  1254.3 1165.38
  1332.0 1204.14  1412.6 1247.64  1467.8 1272.10  1526.2 1289.53  1578.0 1302.68
  1620.1 1320.57  1660.4 1341.00  1707.8 1360.97  1824.8 1398.71  1857.7 1407.40
#Mann= 3 , 0 , 0
       0     0.1       0  1031.9   0.045       0  1046.9     0.1       0
Bank Sta=  1031.9,  1046.9
Exp/Cntr=0.3,0.1

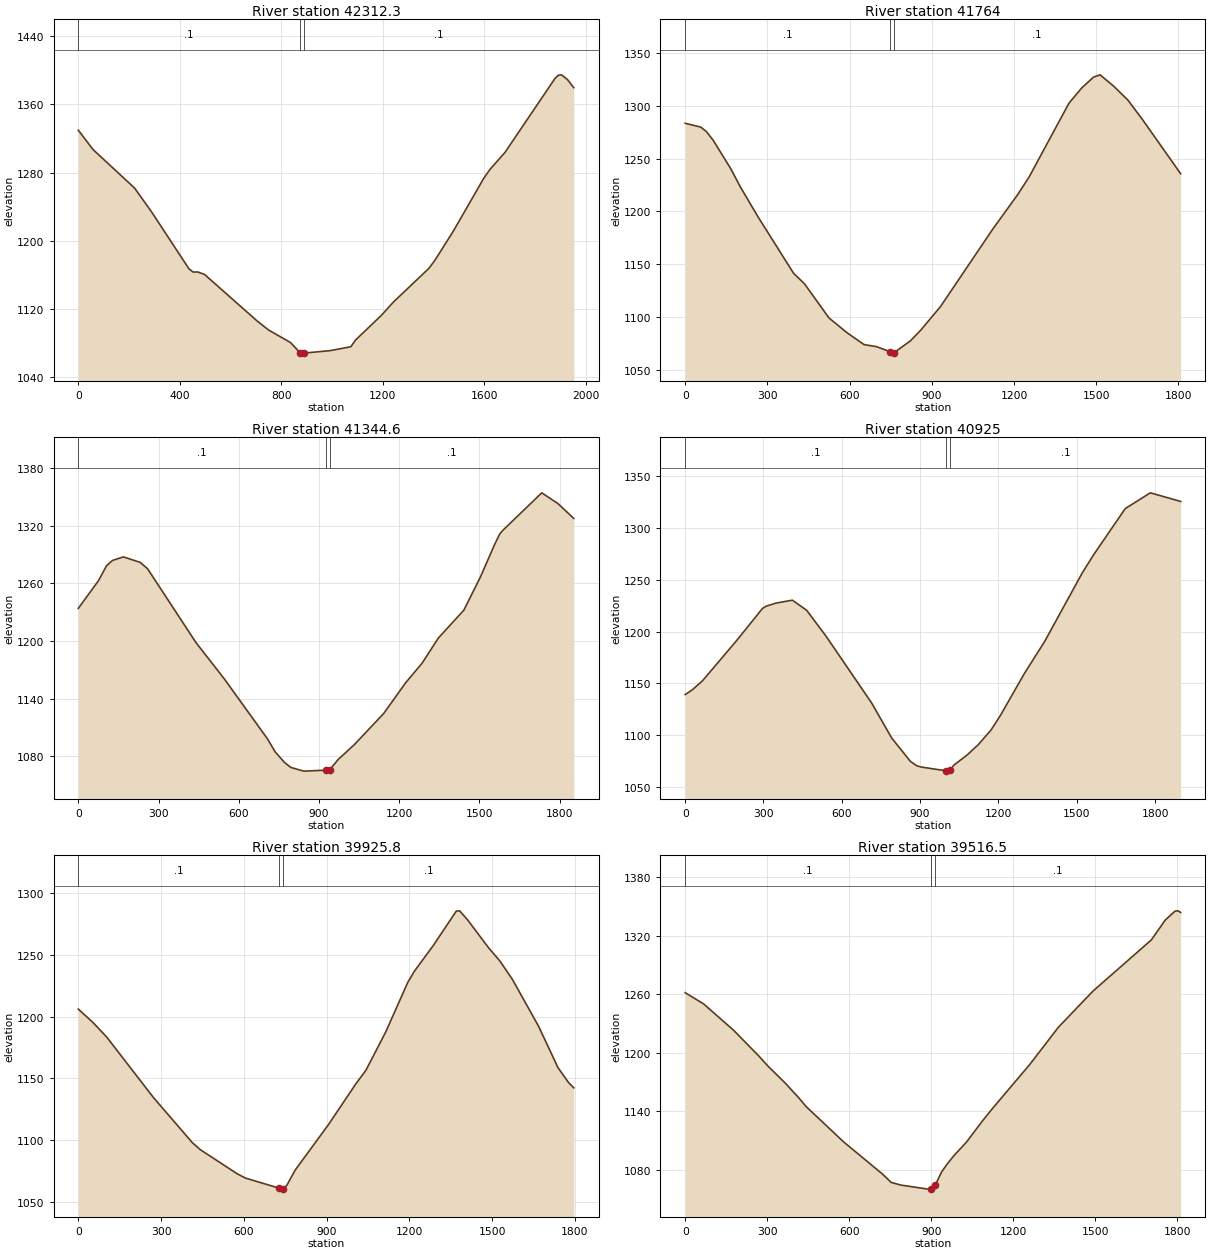
Type RM Length L Ch R = 1 ,42312.3,546.284,548.294,561.306
XS GIS Cut Line= 3
     1667398.195      243408.546     1667142.275      242564.890
     1666598.692      241641.469
#Sta/Elev= 30
       0 1329.78    58.0 1307.05   222.1 1261.75   288.7 1233.92   435.9 1167.18
   452.1 1163.29   470.9 1163.31   497.4 1160.51   704.7 1105.89   749.9 1095.28
   836.7 1080.49   874.1 1068.64   886.9 1068.09   889.1 1068.11   992.4 1071.00
  1074.2 1075.55  1093.5 1083.64  1194.7 1112.42  1242.3 1128.04  1383.0 1167.85
  1406.2 1177.25  1479.3 1211.71  1597.9 1273.07  1622.3 1283.50  1681.9 1303.62
  1878.8 1390.32  1892.6 1394.28  1904.9 1394.74  1928.0 1389.33  1953.2 1379.69
#Mann= 3 , 0 , 0
       0     0.1       0   874.1   0.045       0   889.1     0.1       0
Bank Sta=   874.1,   889.1
Exp/Cntr=0.3,0.1

Type RM Length L Ch R = 1 ,41764,415.924,419.386,422.842
XS GIS Cut Line= 3
     1667554.638      243065.521     1667331.552      242043.150
     1667086.943      241321.506
#Sta/Elev= 30
       0 1283.29    56.8 1279.72    77.5 1275.46   102.3 1267.21   166.1 1240.49
   201.1 1223.34   265.6 1195.01   395.5 1141.64   435.9 1131.48   524.8 1099.41
   590.0 1085.55   652.7 1074.22   698.3 1072.25   745.8 1067.64   760.1 1066.13
   760.8 1066.23   822.4 1077.82   859.4 1087.72   931.9 1110.12  1121.8 1182.99
  1213.8 1215.97  1256.0 1232.88  1400.8 1302.30  1447.3 1316.68  1490.7 1326.97
  1514.5 1329.10  1565.4 1318.02  1616.0 1305.20  1668.2 1287.17  1808.4 1235.66
#Mann= 3 , 0 , 0
       0     0.1       0   745.8   0.045       0   760.8     0.1       0
Bank Sta=   745.8,   760.8
Exp/Cntr=0.3,0.1

Type RM Length L Ch R = 1 ,41344.6,416.393,419.602,422.818
XS GIS Cut Line= 3
     1667835.931      243115.139     1667751.988      242049.596
     1667603.397      241279.408
#Sta/Elev= 30
       0 1233.93    75.5 1262.71   105.6 1278.22   127.7 1283.74   168.8 1287.44
   231.6 1281.70   258.8 1275.22   440.0 1198.40   545.5 1160.79   708.0 1098.10
   735.5 1085.01   770.9 1073.78   794.7 1068.57   842.9 1064.69   925.5 1065.66
   940.5 1066.09   971.0 1076.50  1032.9 1092.36  1142.8 1124.80  1224.4 1156.58
  1285.6 1176.81  1346.7 1203.04  1442.3 1232.16  1504.5 1266.80  1557.2 1300.41
  1576.5 1311.30  1588.5 1315.23  1733.6 1354.04  1794.1 1342.83  1853.2 1327.45
#Mann= 3 , 0 , 0
       0     0.1       0   925.5   0.045       0   940.5     0.1       0
Bank Sta=   925.5,   940.5
Exp/Cntr=0.3,0.1

Type RM Length L Ch R = 1 ,40925,1001.033,999.186,996.269
XS GIS Cut Line= 3
     1668097.118      243147.982     1668173.972      242059.429
     1668140.512      241253.315
#Sta/Elev= 30
       0 1139.28    27.3 1143.87    66.8 1152.73   196.3 1191.19   295.9 1222.38
   310.1 1224.63   348.0 1227.62   410.6 1230.44   465.3 1220.70   539.4 1195.75
   714.5 1131.09   791.4 1097.22   862.8 1074.81   886.6 1070.61   903.3 1069.34
  1000.2 1065.64  1005.7 1065.35  1015.2 1066.74  1029.5 1071.16  1080.0 1080.94
  1122.3 1090.76  1172.2 1105.25  1207.8 1119.17  1299.5 1159.64  1377.0 1190.50
  1521.4 1256.87  1564.3 1274.11  1685.9 1318.88  1782.0 1334.10  1898.1 1325.80
#Mann= 3 , 0 , 0
       0     0.1       0  1000.2   0.045       0  1015.2     0.1       0
Bank Sta=  1000.2,  1015.2
Exp/Cntr=0.3,0.1

Type RM Length L Ch R = 1 ,39925.8,404.498,409.339,413.312
XS GIS Cut Line= 3
     1668945.944      242673.073     1668797.618      241785.330
     1668614.343      240908.827
#Sta/Elev= 30
       0 1206.27    54.7 1195.04   103.5 1183.40   272.1 1134.57   412.8 1098.03
   441.2 1092.37   575.8 1072.68   605.8 1069.19   727.5 1061.04   740.2 1060.23
   742.5 1060.72   755.6 1063.30   786.3 1075.78   907.1 1112.72  1005.6 1145.55
  1042.2 1156.59  1114.2 1187.75  1194.0 1227.90  1217.6 1236.87  1286.5 1257.85
  1369.7 1285.69  1381.9 1285.94  1410.3 1278.75  1486.8 1255.98  1527.1 1245.45
  1572.8 1230.46  1668.1 1192.28  1738.3 1158.77  1776.7 1146.62  1795.5 1142.39
#Mann= 3 , 0 , 0
       0     0.1       0   727.5   0.045       0   742.5     0.1       0
Bank Sta=   727.5,   742.5
Exp/Cntr=0.3,0.1

Type RM Length L Ch R = 1 ,39516.5,404.206,404.193,404.136
XS GIS Cut Line= 3
     1669145.196      242711.220     1669198.221      241804.604
     1669214.344      240901.172
#Sta/Elev= 30
       0 1261.79    67.3 1250.31   176.7 1223.37   269.1 1196.89   302.8 1186.47
   366.8 1168.78   416.3 1153.66   441.7 1145.12   579.5 1108.70   721.1 1075.82
   753.0 1067.25   788.2 1064.45   888.5 1060.29   899.5 1060.47   914.5 1065.00
   917.1 1065.94   937.5 1077.81   955.8 1085.19   983.1 1094.81  1028.2 1108.39
  1087.0 1130.24  1122.5 1142.61  1260.2 1188.23  1364.8 1226.39  1491.4 1263.50
  1704.7 1315.97  1755.4 1336.30  1791.0 1345.40  1802.9 1345.77  1811.7 1344.10
#Mann= 3 , 0 , 0
       0     0.1       0   899.5   0.045       0   914.5     0.1       0
Bank Sta=   899.5,   914.5
Exp/Cntr=0.3,0.1

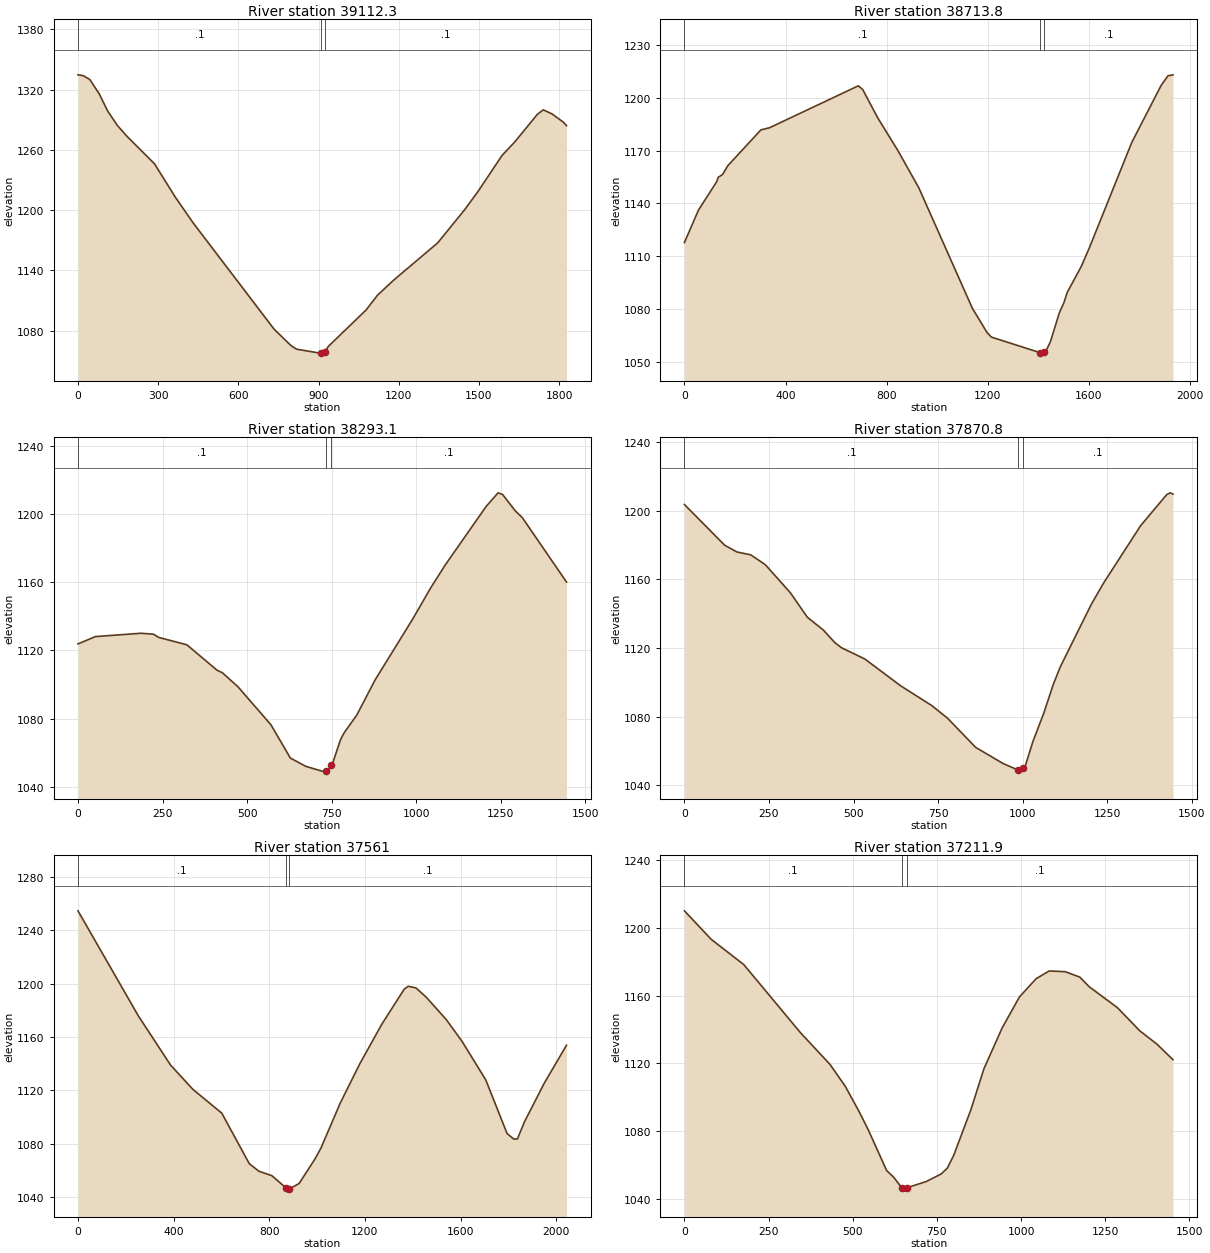
Type RM Length L Ch R = 1 ,39112.3,400.58,398.495,397.111
XS GIS Cut Line= 3
     1669544.514      242734.574     1669598.013      241819.857
     1669614.280      240908.309
#Sta/Elev= 30
       0 1334.66    19.3 1333.86    44.1 1330.06    79.4 1315.80   111.6 1298.45
   146.6 1284.54   183.8 1273.31   286.6 1245.99   364.8 1212.69   430.8 1187.32
   733.5 1081.56   796.9 1065.17   817.7 1061.58   905.3 1057.62   908.8 1057.92
   923.8 1059.15   937.8 1064.58  1078.1 1100.56  1120.6 1115.21  1180.8 1130.18
  1346.1 1167.42  1446.5 1200.24  1497.6 1218.83  1587.2 1254.56  1633.6 1267.59
  1719.4 1295.47  1741.2 1299.79  1773.7 1295.77  1816.1 1287.55  1828.0 1283.99
#Mann= 3 , 0 , 0
       0     0.1       0   908.8   0.045       0   923.8     0.1       0
Bank Sta=   908.8,   923.8
Exp/Cntr=0.3,0.1

Type RM Length L Ch R = 1 ,38713.8,414.437,420.662,424.58
XS GIS Cut Line= 3
     1669865.839      243258.194     1669966.774      242455.142
     1669953.808      241331.111
#Sta/Elev= 30
       0 1117.76    55.4 1136.16   128.3 1152.50   133.9 1154.90   150.3 1156.32
   171.5 1161.41   302.5 1181.81   336.5 1183.01   688.0 1206.87   705.2 1204.86
   765.0 1188.66   844.9 1170.04   927.4 1148.94  1139.5 1080.39  1198.1 1066.47
  1214.7 1063.99    1408 1055.11  1413.7 1054.87    1423 1055.46  1431.9 1056.44
  1448.5 1061.38  1483.7 1077.78  1502.2 1083.68  1514.6 1089.28  1570.9 1104.26
  1603.3 1115.02  1770.5 1174.71  1886.5 1207.08  1913.8 1212.60  1933.5 1213.13
#Mann= 3 , 0 , 0
       0     0.1       0    1408   0.045       0    1423     0.1       0
Bank Sta=    1408,    1423
Exp/Cntr=0.3,0.1

Type RM Length L Ch R = 1 ,38293.1,439.895,422.32,407.946
XS GIS Cut Line= 3
     1670176.537      242708.186     1670332.645      241798.486
     1670373.435      241278.315
#Sta/Elev= 30
       0 1123.78    51.8 1128.07   186.1 1130.02   222.9 1129.50   238.8 1127.58
   322.1 1123.26   411.2 1108.36   427.1 1106.87   473.0 1098.67   570.7 1076.35
   628.1 1056.85   673.4 1052.01   721.2 1049.17   734.6 1049.26   740.3 1049.55
   749.6 1052.51   752.3 1053.27   776.2 1067.53   787.3 1071.69   824.6 1082.05
   878.8 1102.68   989.7 1138.30  1042.8 1156.52  1085.4 1169.86  1206.8 1204.32
  1242.5 1212.38  1255.7 1211.42  1293.6 1201.73  1314.0 1197.85  1444.8 1160.06
#Mann= 3 , 0 , 0
       0     0.1       0   734.6   0.045       0   749.6     0.1       0
Bank Sta=   734.6,   749.6
Exp/Cntr=0.3,0.1

Type RM Length L Ch R = 1 ,37870.8,311.801,309.861,306.046
XS GIS Cut Line= 3
     1671029.368      242762.859     1670648.512      241922.103
     1670390.601      241468.535
#Sta/Elev= 30
       0 1203.63   118.9 1179.91   155.2 1175.96   196.2 1174.28   239.2 1168.55
   313.6 1152.11   363.3 1137.95   410.9 1130.42   444.7 1123.15   464.2 1120.15
   533.3 1113.60   639.3 1097.95   731.6 1086.39   778.3 1079.01   861.0 1062.08
   942.1 1052.65   987.2 1048.78   994.6 1048.19  1002.2 1050.08  1008.3 1051.42
  1030.5 1065.41  1062.9 1082.07  1090.2 1098.41  1111.5 1108.97  1203.1 1145.38
  1239.6 1157.85  1349.2 1191.32  1426.3 1209.40  1436.5 1210.44  1444.8 1209.71
#Mann= 3 , 0 , 0
       0     0.1       0   987.2   0.045       0  1002.2     0.1       0
Bank Sta=   987.2,  1002.2
Exp/Cntr=0.3,0.1

Type RM Length L Ch R = 1 ,37561,355.702,349.057,344.286
XS GIS Cut Line= 3
     1671371.363      242555.400     1670923.209      241816.620
     1670180.294      240901.367
#Sta/Elev= 30
       0 1254.73   252.4 1175.85   387.6 1138.82   480.2 1120.72   601.5 1102.77
   716.3 1064.88   756.4 1059.19   810.7 1055.85   868.6 1046.89   882.1 1045.74
   883.6 1045.81   925.1 1050.02   991.9 1068.65  1016.2 1076.66  1097.0 1110.47
  1178.8 1139.96  1270.8 1169.65  1364.0 1195.85  1380.9 1198.06  1413.1 1196.85
  1455.5 1190.03  1539.8 1173.12  1606.8 1156.51  1705.3 1127.77  1794.4 1087.46
  1822.4 1083.34  1837.5 1083.40  1867.2 1096.32  1950.1 1125.38  2042.9 1153.82
#Mann= 3 , 0 , 0
       0     0.1       0   868.6   0.045       0   883.6     0.1       0
Bank Sta=   868.6,   883.6
Exp/Cntr=0.3,0.1

Type RM Length L Ch R = 1 ,37211.9,296.604,293.416,290.227
XS GIS Cut Line= 3
     1671662.368      241957.676     1670764.990      241283.697
     1670541.790      241041.648
#Sta/Elev= 30
       0 1210.05    79.4 1193.24   176.4 1178.29   344.5 1138.13   432.7 1119.30
   478.0 1106.38   518.6 1091.61   546.1 1080.76   600.8 1056.65   622.1 1052.62
   646.4 1046.31   651.6 1045.68   661.4 1046.52   718.5 1050.18   762.8 1054.63
   781.2 1058.12   800.2 1065.71   851.1 1092.59   890.0 1116.88   944.3 1141.01
   995.2 1159.15  1045.1 1170.00  1083.6 1174.53  1131.1 1174.11  1174.7 1170.90
  1201.9 1165.33  1286.0 1152.92  1353.4 1139.09  1404.0 1131.30  1451.5 1122.11
#Mann= 3 , 0 , 0
       0     0.1       0   646.4   0.045       0   661.4     0.1       0
Bank Sta=   646.4,   661.4
Exp/Cntr=0.3,0.1

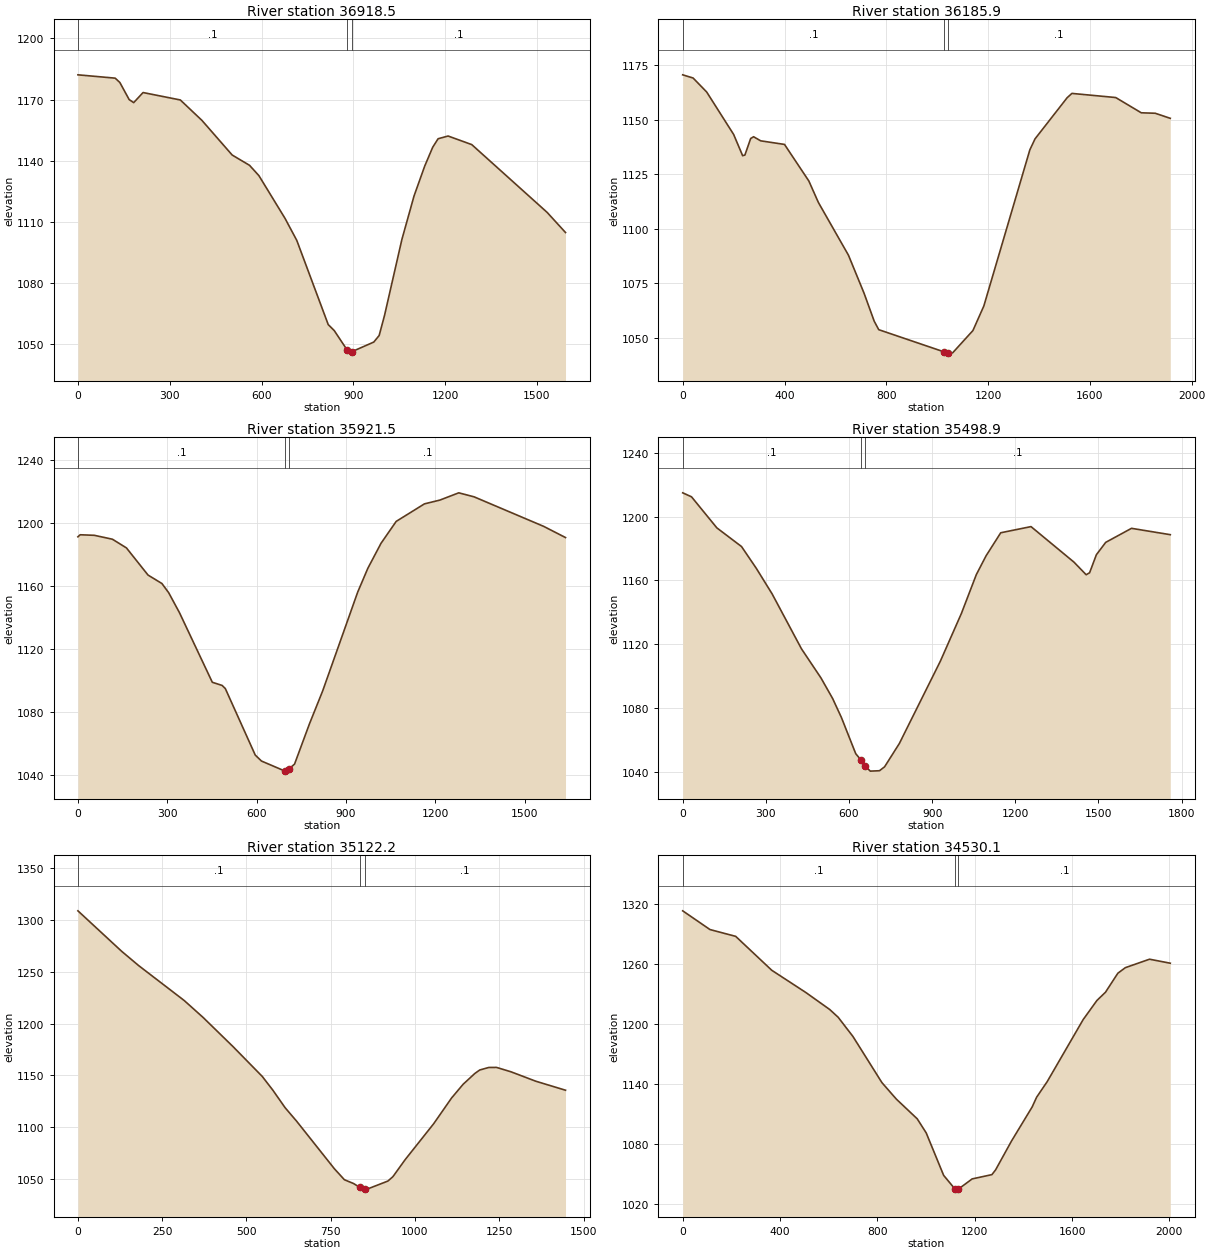
Type RM Length L Ch R = 1 ,36918.5,716.2,732.628,732.237
XS GIS Cut Line= 3
     1671969.860      241843.650     1671360.206      241357.993
     1670644.757      240969.866
#Sta/Elev= 30
       0 1182.12   121.8 1180.49   137.0 1178.37   167.4 1170.00   182.2 1168.49
   212.9 1173.44   334.7 1169.80   405.4 1159.77   504.1 1142.82   560.8 1137.78
   591.5 1132.71   676.8 1111.78   715.3 1100.96   818.0 1059.72   837.7 1056.78
   880.8 1047.05   886.1 1045.74   895.8 1046.48   966.9 1051.16   984.4 1054.37
  1001.9 1064.16  1058.7 1101.43  1098.4 1122.74  1133.3 1137.40  1159.5 1146.65
  1177.1 1150.80  1209.7 1152.13  1287.0 1147.93  1533.3 1114.72  1593.4 1104.85
#Mann= 3 , 0 , 0
       0     0.1       0   880.8   0.045       0   895.8     0.1       0
Bank Sta=   880.8,   895.8
Exp/Cntr=0.3,0.1

Type RM Length L Ch R = 1 ,36185.9,280.902,264.334,265.765
XS GIS Cut Line= 3
     1672160.403      241095.009     1671208.369      240614.089
     1670461.969      240209.172
#Sta/Elev= 30
       0 1170.68    40.9 1169.21    94.2 1162.79   200.2 1143.28   235.5 1133.53
   244.4 1133.82   267.0 1141.42   278.5 1142.24   306.4 1140.36   400.0 1138.71
   495.7 1121.90   533.1 1112.05   651.4 1087.80   712.8 1070.29   752.5 1057.50
   770.3 1053.61  1027.3 1043.40  1040.3 1042.84  1042.3 1042.86  1060.5 1042.95
  1140.3 1053.21  1183.2 1064.50  1364.0 1136.22  1384.2 1141.24  1510.7 1160.19
  1529.3 1162.14  1701.3 1160.25  1801.8 1153.24  1856.4 1153.03  1915.8 1150.70
#Mann= 3 , 0 , 0
       0     0.1       0  1027.3   0.045       0  1042.3     0.1       0
Bank Sta=  1027.3,  1042.3
Exp/Cntr=0.3,0.1

Type RM Length L Ch R = 1 ,35921.5,421.688,422.662,421.955
XS GIS Cut Line= 3
     1671955.709      240800.282     1671172.000      240273.414
     1670508.160      240076.510
#Sta/Elev= 30
       0 1191.23     7.6 1192.52    54.9 1192.18   115.8 1189.70   162.9 1184.18
   235.4 1166.97   282.0 1161.61   304.7 1155.78   340.8 1143.17   451.2 1098.99
   484.1 1097.00   494.8 1095.02   595.3 1052.85   616.2 1049.06   694.5 1042.74
   697.0 1042.67   709.5 1044.21   727.2 1047.12   777.2 1072.61   821.5 1093.46
   939.3 1156.20   973.4 1171.32  1017.5 1187.11  1068.5 1201.01  1163.2 1212.10
  1215.3 1214.52  1278.5 1219.11  1329.9 1216.57  1563.6 1197.84  1636.8 1190.76
#Mann= 3 , 0 , 0
       0     0.1       0   694.5   0.045       0   709.5     0.1       0
Bank Sta=   694.5,   709.5
Exp/Cntr=0.3,0.1

Type RM Length L Ch R = 1 ,35498.9,377.483,376.611,375.475
XS GIS Cut Line= 3
     1672178.876      240468.324     1671344.398      239907.324
     1670621.908      239693.024
#Sta/Elev= 30
       0 1214.87    31.8 1212.37   123.3 1192.90   212.2 1181.22   265.2 1167.66
   322.5 1151.60   428.5 1117.15   498.8 1098.92   541.0 1086.00   572.8 1074.05
   624.2 1051.48   644.3 1047.28   659.3 1043.59   676.7 1040.54   710.0 1040.79
   728.4 1043.26   781.6 1057.84   929.4 1109.35  1005.5 1139.32  1059.3 1163.63
  1094.4 1175.39  1147.4 1189.85  1256.6 1193.71  1411.5 1171.47  1455.6 1163.56
  1468.0 1164.81  1492.4 1176.09  1526.1 1183.84  1619.2 1192.63  1759.1 1188.65
#Mann= 3 , 0 , 0
       0     0.1       0   644.3   0.045       0   659.3     0.1       0
Bank Sta=   644.3,   659.3
Exp/Cntr=0.3,0.1

Type RM Length L Ch R = 1 ,35122.2,589.375,592.143,587.442
XS GIS Cut Line= 3
     1672402.044      240136.365     1671617.901      239707.626
     1671075.399      239600.904
#Sta/Elev= 30
       0 1309.05   130.2 1269.77   180.0 1256.13   315.3 1222.30   371.1 1206.00
   460.5 1177.59   547.0 1148.81   578.4 1135.52   614.7 1118.61   648.9 1105.53
   761.0 1059.50   790.6 1048.92   817.7 1045.26     836 1041.58   844.7 1039.83
     851 1039.85   858.3 1039.87   919.7 1047.64   934.6 1051.90   970.9 1068.36
  1055.6 1103.15  1108.7 1128.03  1143.0 1141.31  1177.9 1151.80  1192.2 1155.07
  1218.7 1157.50  1241.8 1157.59  1284.9 1153.33  1358.1 1144.26  1446.6 1135.51
#Mann= 3 , 0 , 0
       0     0.1       0     836   0.045       0     851     0.1       0
Bank Sta=     836,     851
Exp/Cntr=0.3,0.1

Type RM Length L Ch R = 1 ,34530.1,683.105,696.824,715.654
XS GIS Cut Line= 3
     1672625.211      239804.407     1671689.193      239175.145
     1670849.402      238926.052
#Sta/Elev= 30
       0 1312.94   112.1 1294.25   217.8 1287.45   366.0 1253.60   505.6 1231.49
   604.1 1214.46   638.8 1206.73   699.6 1187.53   818.7 1141.47   878.0 1124.99
   963.7 1105.35  1000.6 1091.32  1072.4 1048.88  1118.1 1035.52  1132.7 1035.15
  1133.1 1035.22  1189.7 1045.36  1270.7 1049.62  1285.8 1054.34  1351.2 1083.13
  1436.0 1117.11  1454.6 1126.94  1498.0 1142.46  1645.6 1204.32  1702.3 1223.46
  1737.6 1231.72  1788.3 1250.67  1819.2 1256.21  1918.5 1264.65  2003.8 1260.65
#Mann= 3 , 0 , 0
       0     0.1       0  1118.1   0.045       0  1133.1     0.1       0
Bank Sta=  1118.1,  1133.1
Exp/Cntr=0.3,0.1