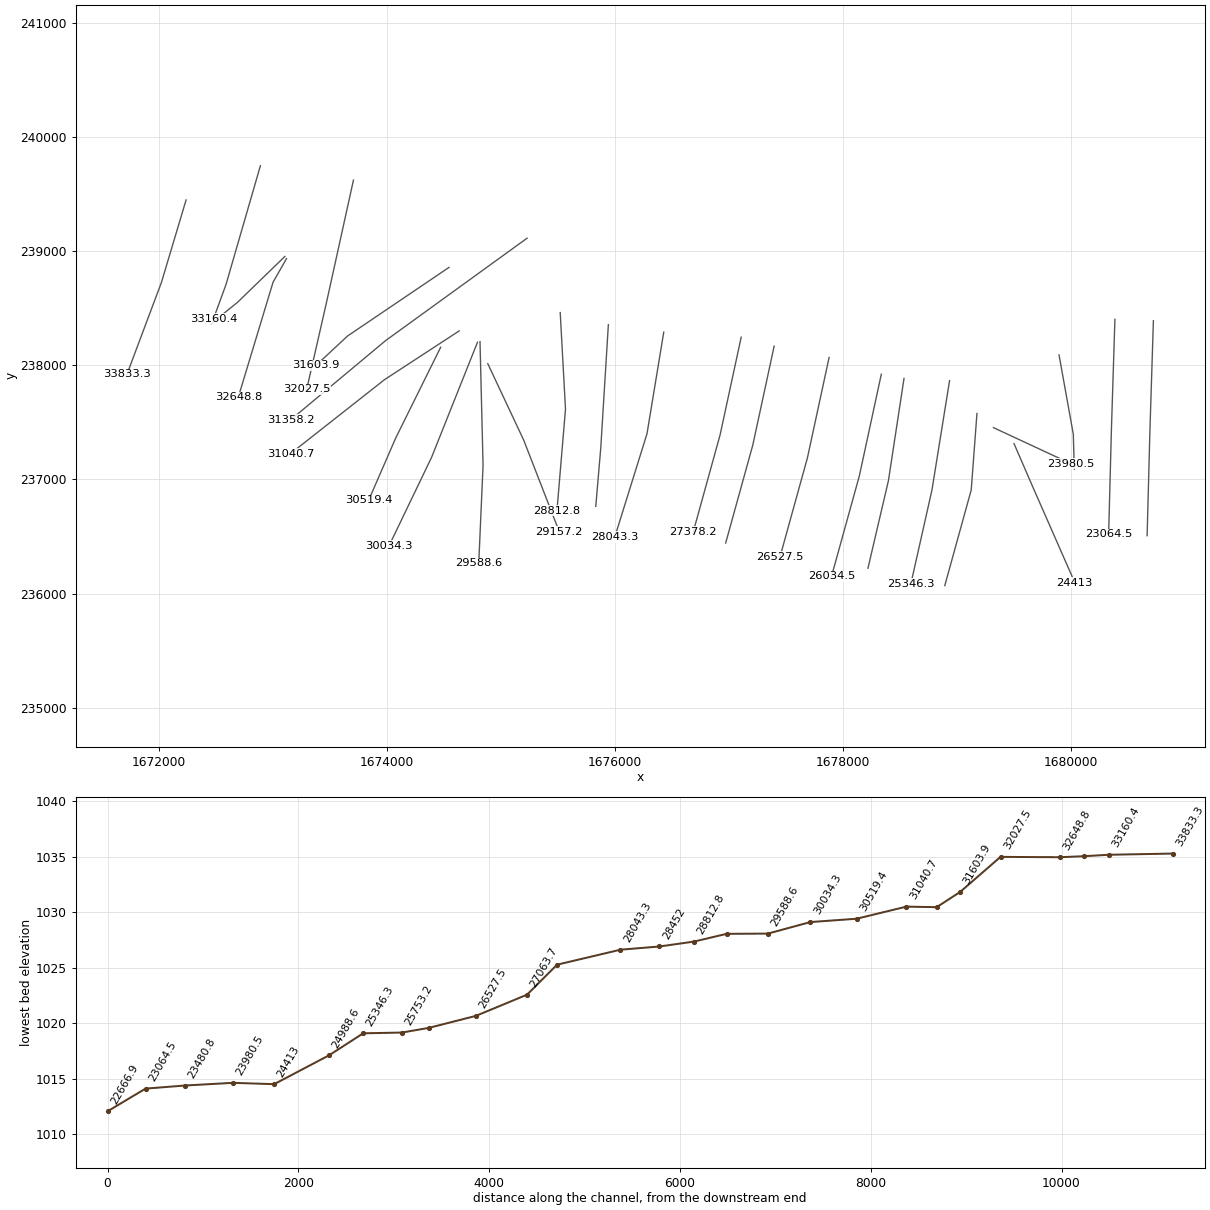
HEC-RAS study KinchloCr.prj: KinchloCr

--- KinchloCr.g01 (geometry) --- (continued)

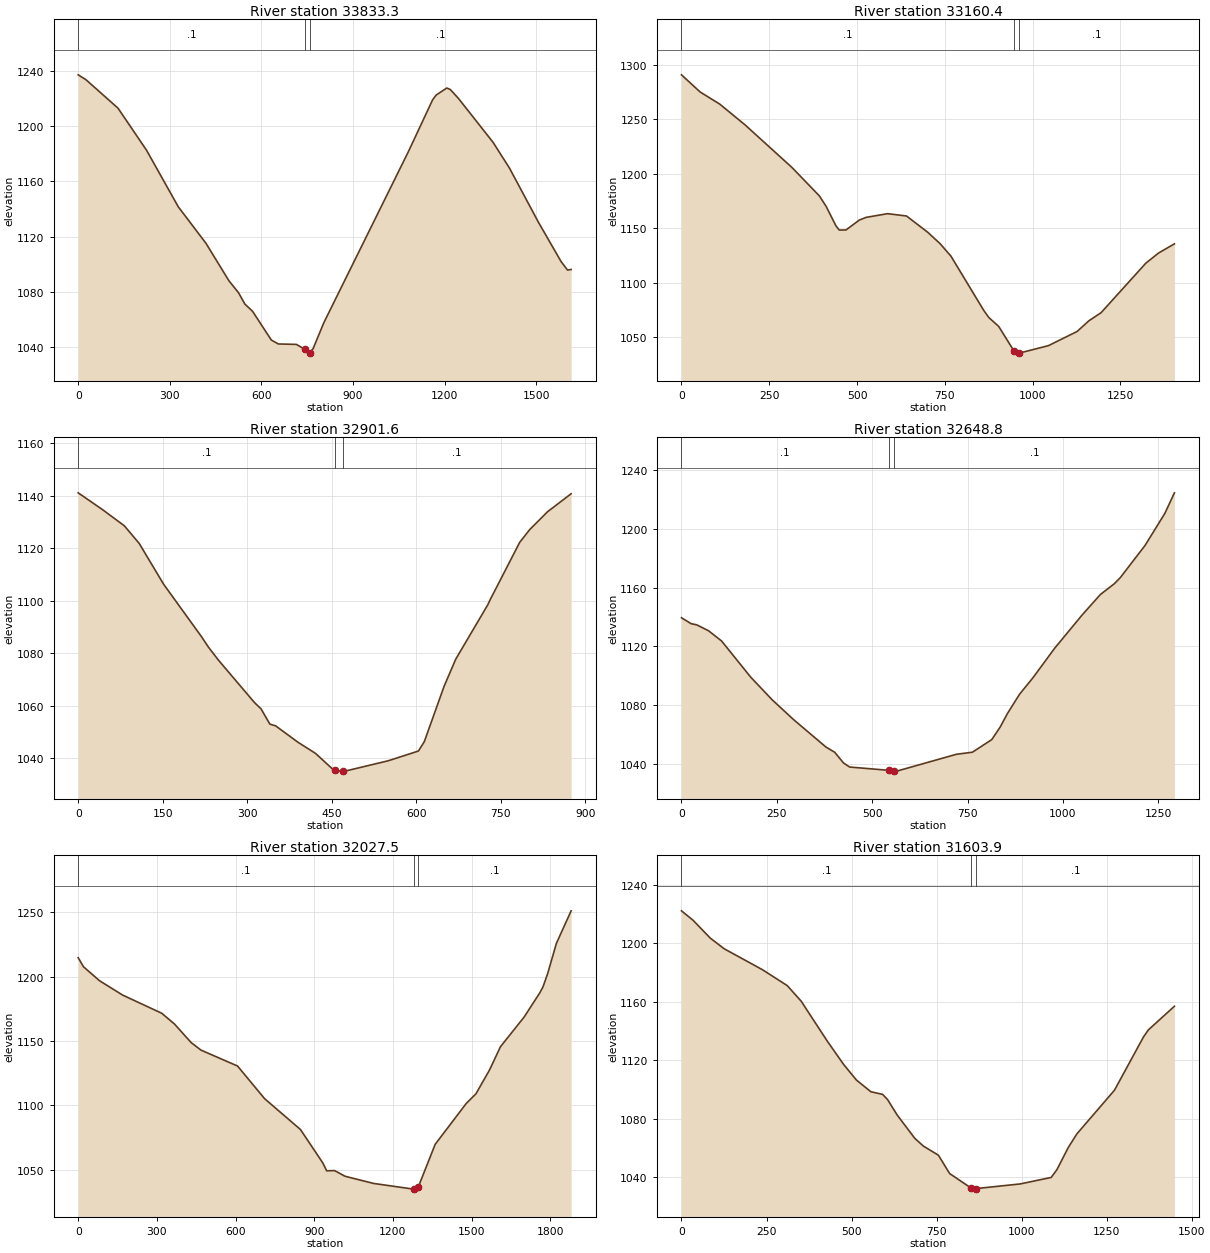
Type RM Length L Ch R = 1 ,33833.3,670.256,672.832,677.719
XS GIS Cut Line= 3
     1672238.715      239450.232     1672022.873      238728.197
     1671720.533      237922.715
#Sta/Elev= 30
       0 1237.48    25.3 1233.96   130.3 1213.28   223.6 1182.78   327.8 1141.57
   418.3 1115.12   493.4 1087.92   525.1 1079.16   545.8 1070.92   570.9 1065.70
   632.5 1044.78   655.5 1041.95   714.4 1041.64   742.8 1038.00   756.5 1035.30
   757.8 1035.63   769.2 1038.56   804.1 1057.31  1081.2 1181.69  1160.6 1219.37
  1172.1 1222.79  1206.9 1227.90  1218.5 1226.78  1245.1 1220.33  1358.3 1188.48
  1412.1 1169.74  1507.1 1130.33  1581.1 1101.84  1602.2 1095.66  1614.0 1096.06
#Mann= 3 , 0 , 0
       0     0.1       0   742.8   0.045       0   757.8     0.1       0
Bank Sta=   742.8,   757.8
Exp/Cntr=0.3,0.1

Type RM Length L Ch R = 1 ,33160.4,270.48,258.887,247.294
XS GIS Cut Line= 3
     1672890.485      239750.251     1672588.778      238708.629
     1672479.013      238408.426
#Sta/Elev= 30
       0 1290.84    53.3 1275.04   109.0 1263.94   180.9 1244.91   315.1 1205.60
   392.7 1179.64   411.8 1170.14   439.7 1152.30   449.3 1148.24   468.5 1148.30
   506.8 1157.48   526.0 1159.90   587.2 1163.30   641.0 1161.15   701.2 1146.28
   736.9 1135.66   767.6 1124.24   861.5 1074.16   875.6 1067.86   903.6 1059.71
   947.2 1037.12   962.0 1035.19   962.2 1035.21  1045.1 1042.05  1126.9 1055.06
  1160.2 1064.84  1195.2 1072.33  1322.7 1117.84  1359.0 1127.16  1404.1 1135.57
#Mann= 3 , 0 , 0
       0     0.1       0   947.2   0.045       0   962.2     0.1       0
Bank Sta=   947.2,   962.2
Exp/Cntr=0.3,0.1

Type RM Length L Ch R = 1 ,32901.6,241.329,252.725,264.121
XS GIS Cut Line= 3
     1673105.056      238955.211     1672690.759      238553.565
     1672458.843      238366.582
#Sta/Elev= 30
       0 1141.11    43.1 1134.72    81.9 1128.55   108.3 1121.83   151.8 1106.23
   218.6 1086.37   231.4 1082.24   249.0 1077.34   313.0 1061.16   324.5 1058.81
   340.2 1052.98   350.6 1052.29   389.9 1046.09   421.2 1041.82   452.0 1035.76
   455.1 1035.39   468.9 1035.06   470.1 1035.06   473.6 1035.06   550.2 1039.00
   603.9 1042.72   614.3 1046.28   649.4 1067.37   670.1 1077.72   726.9 1098.42
   731.2 1100.38   783.6 1122.23   801.4 1127.10   832.8 1133.86   874.9 1140.76
#Mann= 3 , 0 , 0
       0     0.1       0   455.1   0.045       0   470.1     0.1       0
Bank Sta=   455.1,   470.1
Exp/Cntr=0.3,0.1

Type RM Length L Ch R = 1 ,32648.8,619.57,621.308,623.072
XS GIS Cut Line= 3
     1673119.601      238936.167     1673001.602      238729.558
     1672696.361      237720.449
#Sta/Elev= 30
       0 1139.50    25.5 1135.45    40.1 1134.67    71.2 1130.60   105.2 1123.65
   181.7 1098.96   237.9 1083.54   293.6 1070.14   378.6 1051.41   401.7 1047.82
   424.9 1040.50   440.7 1037.77   542.9 1035.52   557.9 1035.14   564.3 1034.97
   720.4 1046.43   762.6 1047.86   813.4 1056.47   835.4 1065.00   854.7 1074.34
   886.5 1087.48   920.7 1098.40   978.0 1118.65  1050.0 1141.32  1098.1 1155.36
  1134.5 1162.67  1150.5 1166.92  1215.3 1188.84  1267.1 1210.65  1292.2 1224.66
#Mann= 3 , 0 , 0
       0     0.1       0   542.9   0.045       0   557.9     0.1       0
Bank Sta=   542.9,   557.9
Exp/Cntr=0.3,0.1

Type RM Length L Ch R = 1 ,32027.5,441.618,423.577,403.935
XS GIS Cut Line= 3
     1673706.603      239624.322     1673466.554      238535.452
     1673296.337      237789.704
#Sta/Elev= 30
       0 1214.61    20.4 1207.54    81.5 1196.71   169.5 1185.60   318.7 1171.48
   367.0 1163.18   431.0 1148.70   468.3 1142.89   607.8 1130.52   710.9 1105.20
   847.5 1081.30   932.6 1055.43   947.7 1049.23   977.7 1049.39  1017.7 1044.99
  1127.0 1039.40  1279.3 1035.00  1281.7 1035.21  1296.7 1036.48  1361.4 1069.76
  1479.8 1101.46  1516.8 1108.94  1569.1 1127.62  1610.4 1145.52  1700.8 1168.59
  1760.0 1187.20  1772.6 1191.96  1790.5 1202.34  1823.6 1225.67  1879.9 1250.98
#Mann= 3 , 0 , 0
       0     0.1       0  1281.7   0.045       0  1296.7     0.1       0
Bank Sta=  1281.7,  1296.7
Exp/Cntr=0.3,0.1

Type RM Length L Ch R = 1 ,31603.9,242.137,245.758,250.953
XS GIS Cut Line= 3
     1674544.639      238859.239     1673655.156      238257.822
     1673380.176      238001.887
#Sta/Elev= 30
       0 1222.26    34.1 1215.80    84.4 1203.65   125.9 1196.24   238.2 1181.96
   310.9 1171.10   351.9 1160.45   429.1 1132.97   477.0 1117.07   514.4 1106.48
   556.7 1098.49   591.3 1096.67   605.8 1093.17   634.1 1082.60   685.8 1066.65
   711.0 1061.34   755.4 1055.05   788.5 1042.50   852.3 1032.46   855.6 1031.84
   867.3 1032.23   995.7 1035.38  1087.0 1039.83  1103.8 1045.13  1137.4 1060.37
  1162.7 1069.67  1273.2 1099.55  1358.3 1135.92  1372.7 1140.78  1449.4 1156.97
#Mann= 3 , 0 , 0
       0     0.1       0   852.3   0.045       0   867.3     0.1       0
Bank Sta=   852.3,   867.3
Exp/Cntr=0.3,0.1

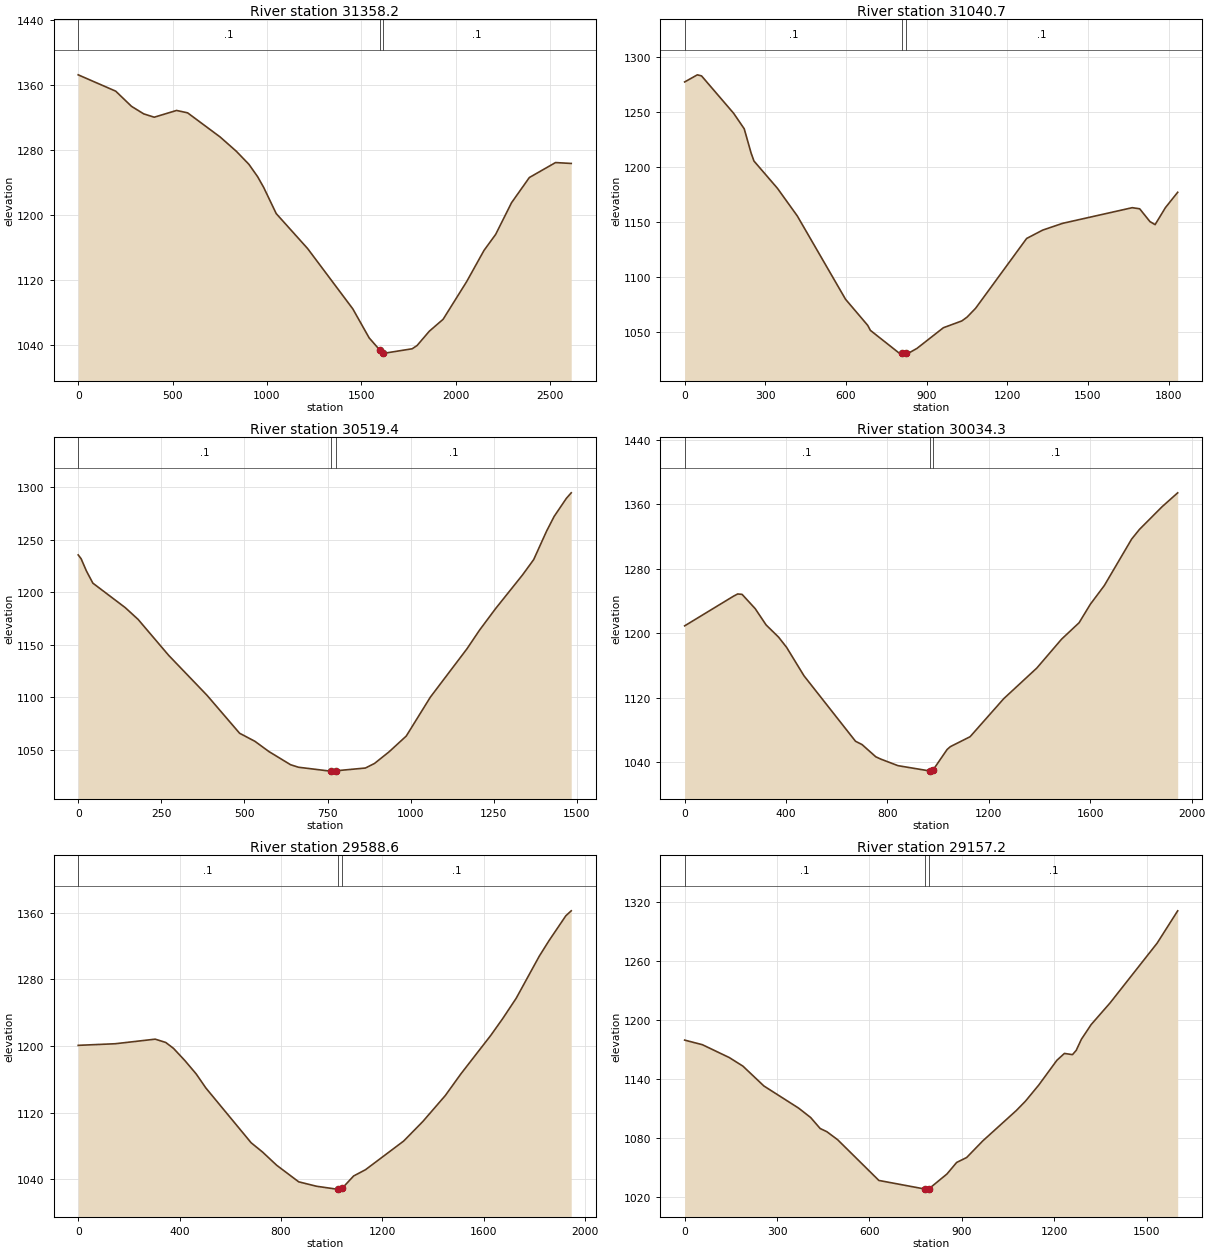
Type RM Length L Ch R = 1 ,31358.2,316.865,317.483,317.93
XS GIS Cut Line= 3
     1675229.240      239115.165     1673989.405      238218.005
     1673159.332      237525.569
#Sta/Elev= 30
       0 1372.62   198.9 1352.52   282.5 1333.86   347.0 1324.63   402.8 1320.52
   521.1 1328.82   579.7 1325.87   751.4 1296.28   837.8 1278.60   904.5 1262.54
   950.4 1247.39   982.3 1234.27  1048.9 1202.02  1215.0 1159.08  1454.6 1084.87
  1541.0 1049.26  1597.3 1034.31  1612.3 1030.61  1625.1 1030.47  1769.0 1035.82
  1794.9 1039.81  1859.8 1057.41  1932.9 1072.08  2057.5 1118.35  2149.6 1156.80
  2211.1 1176.40  2295.1 1215.33  2389.5 1246.33  2528.3 1264.76  2611.4 1263.66
#Mann= 3 , 0 , 0
       0     0.1       0  1597.3   0.045       0  1612.3     0.1       0
Bank Sta=  1597.3,  1612.3
Exp/Cntr=0.3,0.1

Type RM Length L Ch R = 1 ,31040.7,513.339,521.335,529.502
XS GIS Cut Line= 3
     1674634.213      238302.600     1673980.283      237875.948
     1673152.910      237225.114
#Sta/Elev= 30
       0 1277.20    47.3 1283.67    62.9 1282.67   182.1 1248.69   221.5 1234.59
   247.2 1212.44   257.9 1205.20   345.0 1180.47   418.8 1155.34   598.3 1079.52
   680.7 1055.81   690.8 1051.21   797.9 1030.52   807.8 1030.77   822.8 1031.01
   835.9 1030.97   863.7 1034.78   962.2 1053.63  1030.8 1059.82  1050.2 1063.26
  1082.1 1071.35  1271.7 1134.80  1331.2 1142.40  1405.6 1148.58  1664.5 1162.82
  1692.2 1161.80  1730.3 1150.18  1749.5 1147.40  1787.9 1162.86  1833.5 1176.83
#Mann= 3 , 0 , 0
       0     0.1       0   807.8   0.045       0   822.8     0.1       0
Bank Sta=   807.8,   822.8
Exp/Cntr=0.3,0.1

Type RM Length L Ch R = 1 ,30519.4,483.022,485.046,486.429
XS GIS Cut Line= 3
     1674471.347      238158.752     1674076.982      237362.741
     1673839.661      236817.234
#Sta/Elev= 30
       0 1235.49     8.7 1231.95    24.8 1220.17    44.2 1208.58   141.5 1185.27
   180.1 1174.09   272.6 1139.64   387.8 1101.62   485.5 1065.55   531.7 1057.85
   573.7 1048.10   638.8 1035.56   662.7 1033.13   758.1 1029.43   760.6 1029.56
   775.6 1029.77   864.0 1032.38   891.2 1036.70   935.0 1047.76   986.9 1062.84
  1059.5 1099.98  1169.6 1146.03  1207.2 1163.73  1255.2 1184.14  1337.0 1216.55
  1370.3 1231.05  1409.0 1258.14  1431.9 1272.22  1468.8 1289.50  1483.2 1294.68
#Mann= 3 , 0 , 0
       0     0.1       0   760.6   0.045       0   775.6     0.1       0
Bank Sta=   760.6,   775.6
Exp/Cntr=0.3,0.1

Type RM Length L Ch R = 1 ,30034.3,431.132,445.736,456.713
XS GIS Cut Line= 3
     1674794.452      238202.926     1674392.543      237195.716
     1674019.658      236420.366
#Sta/Elev= 30
       0 1209.38   193.5 1246.35   209.4 1248.96   226.5 1248.45   278.2 1230.76
   321.3 1210.51   370.5 1195.40   402.0 1182.75   470.9 1147.34   674.0 1066.18
   699.5 1062.14   754.0 1046.90   773.9 1044.03   841.4 1035.91   965.9 1029.38
   971.3 1029.13   980.9 1031.02  1035.2 1055.95  1048.0 1059.49  1126.0 1071.84
  1258.6 1119.03  1389.2 1157.05  1486.9 1192.90  1555.8 1213.22  1600.2 1236.17
  1655.3 1259.35  1763.2 1317.05  1793.6 1328.90  1883.2 1357.18  1944.8 1374.44
#Mann= 3 , 0 , 0
       0     0.1       0   965.9   0.045       0   980.9     0.1       0
Bank Sta=   965.9,   980.9
Exp/Cntr=0.3,0.1

Type RM Length L Ch R = 1 ,29588.6,429.605,431.394,436.829
XS GIS Cut Line= 3
     1674816.547      238208.320     1674843.287      237124.213
     1674805.496      236264.688
#Sta/Elev= 30
       0 1200.71   146.0 1202.64   303.8 1208.14   345.3 1204.18   375.9 1197.11
   421.0 1182.39   465.6 1166.33   503.8 1149.44   682.2 1083.75   727.3 1072.60
   782.8 1056.79   869.8 1036.86   939.8 1031.56  1019.0 1028.09  1024.9 1028.28
  1039.9 1029.71  1050.5 1032.11  1086.4 1043.86  1133.5 1051.43  1283.9 1085.82
  1359.2 1109.19  1448.1 1140.45  1509.4 1166.38  1627.5 1212.68  1673.8 1232.52
  1727.7 1257.23  1818.9 1307.84  1857.1 1326.37  1923.5 1356.25  1944.8 1362.22
#Mann= 3 , 0 , 0
       0     0.1       0  1024.9   0.045       0  1039.9     0.1       0
Bank Sta=  1024.9,  1039.9
Exp/Cntr=0.3,0.1

Type RM Length L Ch R = 1 ,29157.2,355.742,344.406,333.103
XS GIS Cut Line= 3
     1674884.681      238015.261     1675199.504      237345.446
     1675511.241      236543.554
#Sta/Elev= 30
       0 1179.73    57.5 1175.05   144.8 1161.97   189.1 1153.24   257.3 1133.02
   369.7 1110.57   409.0 1100.94   439.9 1089.76   461.5 1086.54   496.5 1078.38
   630.5 1036.90   778.8 1028.22   782.0 1028.07   793.8 1028.61   851.7 1043.53
   882.9 1055.20   915.4 1060.22   967.8 1077.16  1076.9 1108.13  1106.5 1117.65
  1149.7 1134.08  1208.4 1159.21  1232.8 1166.16  1258.9 1164.93  1271.0 1169.24
  1287.8 1180.52  1319.4 1195.45  1381.2 1217.64  1533.8 1278.40  1600.5 1311.29
#Mann= 3 , 0 , 0
       0     0.1       0   778.8   0.045       0   793.8     0.1       0
Bank Sta=   778.8,   793.8
Exp/Cntr=0.3,0.1

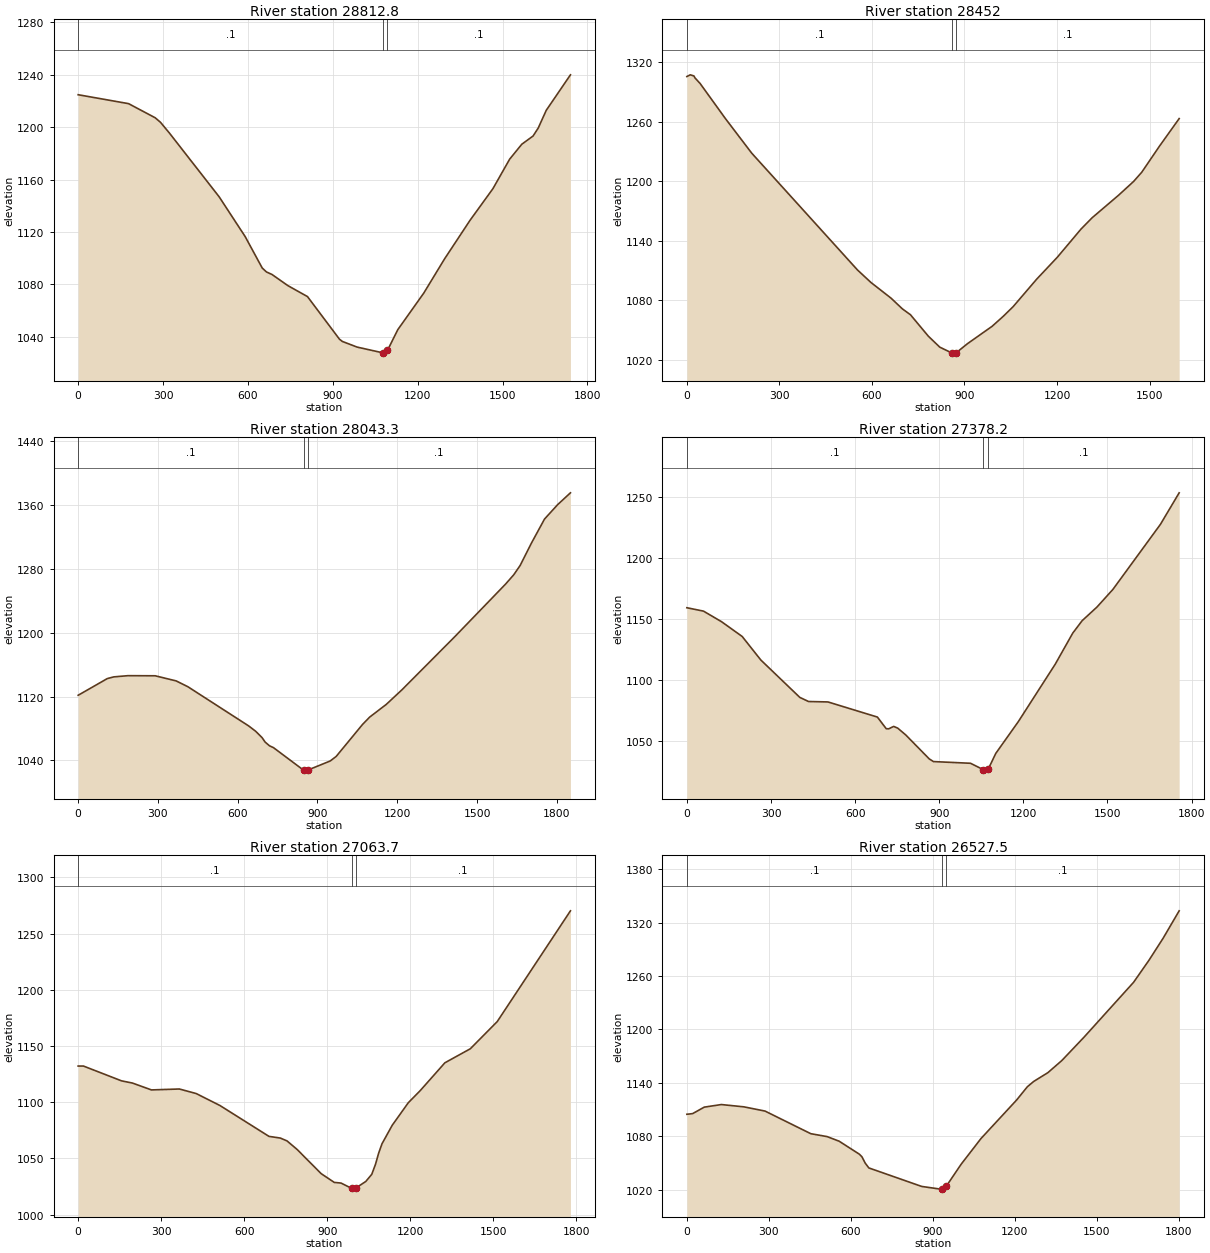
Type RM Length L Ch R = 1 ,28812.8,359.484,360.792,362.05
XS GIS Cut Line= 3
     1675519.885      238463.231     1675566.271      237617.251
     1675491.358      236727.606
#Sta/Elev= 30
       0 1224.77   178.2 1217.95   272.4 1207.15   291.1 1203.69   323.1 1195.34
   498.3 1146.81   590.4 1116.38   650.6 1092.39   665.4 1089.41   685.3 1087.43
   741.1 1078.96   810.6 1070.55   923.7 1037.99   933.7 1036.31   985.7 1032.00
  1075.8 1027.65  1079.7 1027.37  1090.8 1029.67  1096.6 1030.88  1129.8 1045.30
  1221.4 1073.17  1295.4 1099.48  1385.1 1128.83  1466.1 1153.04  1525.1 1175.53
  1568.1 1186.96  1607.9 1193.23  1626.2 1199.34  1654.5 1212.86  1740.0 1239.97
#Mann= 3 , 0 , 0
       0     0.1       0  1075.8   0.045       0  1090.8     0.1       0
Bank Sta=  1075.8,  1090.8
Exp/Cntr=0.3,0.1

Type RM Length L Ch R = 1 ,28452,410.654,408.652,406.649
XS GIS Cut Line= 3
     1675942.148      238356.581     1675875.642      237277.845
     1675831.822      236764.527
#Sta/Elev= 30
       0 1305.39    11.0 1307.09    22.9 1305.95    26.1 1304.06    43.0 1298.34
   125.1 1262.98   210.2 1228.25   553.2 1110.61   597.3 1097.92   661.8 1082.30
   698.6 1071.50   724.8 1065.59   782.9 1043.96   819.9 1032.95   858.5 1027.18
   860.0 1026.93   873.5 1027.37   909.8 1036.46   989.6 1053.94  1025.5 1063.92
  1057.8 1073.73  1133.8 1101.29  1200.8 1123.39  1277.9 1151.84  1314.0 1163.25
  1399.0 1185.73  1448.2 1199.72  1474.8 1209.07  1531.3 1234.90  1596.0 1263.03
#Mann= 3 , 0 , 0
       0     0.1       0   858.5   0.045       0   873.5     0.1       0
Bank Sta=   858.5,   873.5
Exp/Cntr=0.3,0.1

Type RM Length L Ch R = 1 ,28043.3,667.742,665.172,662.601
XS GIS Cut Line= 3
     1676427.977      238291.423     1676280.906      237400.630
     1675998.457      236495.269
#Sta/Elev= 30
       0 1121.61   109.6 1142.52   133.9 1144.63   187.3 1146.15   289.7 1146.01
   368.6 1139.59   413.2 1132.19   640.9 1083.31   667.1 1076.66   691.4 1068.66
   703.2 1062.98   719.3 1058.39   734.6 1056.01   849.1 1027.48   852.6 1026.64
   864.1 1028.01   947.8 1039.34   970.2 1045.01  1069.5 1085.12  1096.3 1094.30
  1159.0 1110.28  1217.9 1128.57  1414.7 1194.44  1606.6 1260.60  1637.9 1272.42
  1662.1 1284.17  1704.0 1311.81  1753.7 1342.26  1803.4 1360.39  1851.2 1375.09
#Mann= 3 , 0 , 0
       0     0.1       0   849.1   0.045       0   864.1     0.1       0
Bank Sta=   849.1,   864.1
Exp/Cntr=0.3,0.1

Type RM Length L Ch R = 1 ,27378.2,314.65,314.508,314.365
XS GIS Cut Line= 3
     1677107.092      238247.234     1676921.976      237390.526
     1676687.349      236543.265
#Sta/Elev= 30
       0 1159.24    59.3 1156.46   123.9 1147.76   197.3 1135.67   263.8 1116.37
   402.8 1085.73   433.9 1082.36   503.2 1082.01   679.4 1069.61   711.0 1060.06
   719.8 1059.97   737.5 1061.95   751.8 1060.55   780.7 1054.92   864.4 1035.30
   879.5 1033.12  1011.5 1031.73  1057.7 1026.44  1064.8 1025.29  1072.7 1027.30
  1078.8 1028.88  1101.6 1039.82  1182.1 1065.90  1313.6 1112.94  1376.2 1138.47
  1409.6 1148.62  1462.6 1159.84  1519.3 1174.26  1688.8 1227.62  1755.6 1253.45
#Mann= 3 , 0 , 0
       0     0.1       0  1057.7   0.045       0  1072.7     0.1       0
Bank Sta=  1057.7,  1072.7
Exp/Cntr=0.3,0.1

Type RM Length L Ch R = 1 ,27063.7,535.573,536.162,536.744
XS GIS Cut Line= 3
     1677396.204      238169.013     1677208.665      237301.091
     1676970.977      236442.773
#Sta/Elev= 30
       0 1132.10    19.0 1132.12   156.7 1118.94   195.9 1117.00   264.9 1110.87
   365.7 1111.69   426.5 1107.64   512.1 1097.02   689.5 1069.53   730.4 1068.04
   754.7 1065.49   791.1 1057.90   878.0 1036.36   925.2 1028.59   949.9 1027.97
   988.5 1023.23   993.6 1022.59  1003.5 1023.62  1039.2 1029.41  1060.8 1035.77
  1074.2 1044.62  1085.4 1054.38  1097.7 1062.92  1134.7 1079.42  1192.7 1099.45
  1235.4 1110.13  1325.0 1135.02  1416.8 1147.48  1514.1 1171.68  1778.6 1270.24
#Mann= 3 , 0 , 0
       0     0.1       0   988.5   0.045       0  1003.5     0.1       0
Bank Sta=   988.5,  1003.5
Exp/Cntr=0.3,0.1

Type RM Length L Ch R = 1 ,26527.5,490.408,492.966,496.656
XS GIS Cut Line= 3
     1677878.058      238069.378     1677688.096      237190.242
     1677447.346      236320.868
#Sta/Elev= 30
       0 1104.71    21.1 1105.45    63.7 1112.74   126.1 1115.63   208.3 1113.07
   286.0 1108.31   453.4 1082.92   513.2 1079.65   557.1 1074.50   631.1 1059.92
   640.6 1057.00   652.4 1049.99   665.9 1044.48   859.2 1023.71   928.4 1020.68
   934.4 1020.95   941.4 1021.26   949.4 1023.98  1003.7 1048.64  1076.4 1077.51
  1206.7 1120.73  1245.9 1135.59  1269.4 1141.63  1321.0 1151.41  1372.0 1165.00
  1454.2 1191.55  1634.8 1252.90  1691.6 1277.90  1743.0 1302.47  1801.5 1333.12
#Mann= 3 , 0 , 0
       0     0.1       0   934.4   0.045       0   949.4     0.1       0
Bank Sta=   934.4,   949.4
Exp/Cntr=0.3,0.1

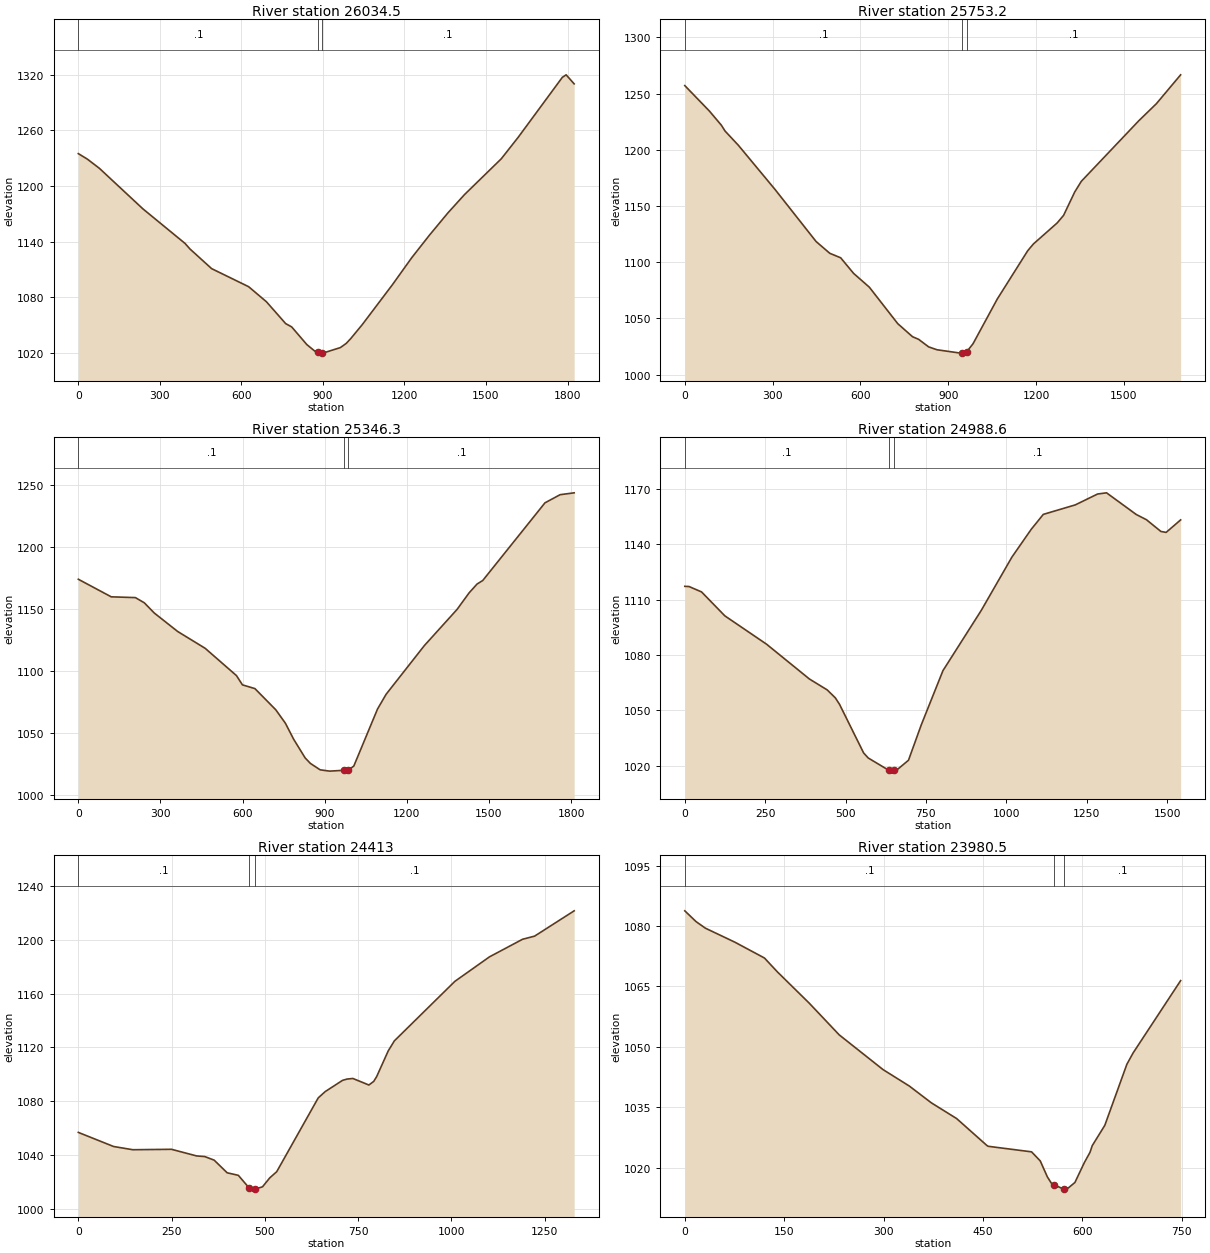
Type RM Length L Ch R = 1 ,26034.5,283.066,281.354,278.51
XS GIS Cut Line= 3
     1678335.909      237922.642     1678143.524      237032.293
     1677899.712      236151.862
#Sta/Elev= 30
       0 1234.79    33.4 1228.83    77.5 1218.94   237.8 1175.16   392.8 1137.89
   410.7 1131.96   490.5 1110.73   626.7 1091.24   692.3 1074.98   762.9 1051.45
   785.1 1047.88   840.8 1028.82   870.0 1021.80   882.7 1020.42   897.7 1019.69
   899.6 1019.60   964.2 1025.57   985.5 1030.01  1002.4 1035.29  1045.1 1050.47
  1156.2 1093.56  1226.4 1122.35  1291.1 1146.50  1359.2 1170.59  1420.8 1190.53
  1556.3 1229.21  1618.5 1252.37  1780.9 1317.03  1795.0 1319.78  1824.5 1310.03
#Mann= 3 , 0 , 0
       0     0.1       0   882.7   0.045       0   897.7     0.1       0
Bank Sta=   882.7,   897.7
Exp/Cntr=0.3,0.1

Type RM Length L Ch R = 1 ,25753.2,406.301,406.871,406.591
XS GIS Cut Line= 3
     1678535.004      237885.444     1678398.414      236989.886
     1678218.886      236222.268
#Sta/Elev= 30
       0 1257.09    84.2 1234.42   125.0 1221.84   137.5 1216.70   183.1 1204.00
   307.9 1164.87   448.7 1118.41   495.4 1107.96   532.7 1103.95   576.8 1090.08
   630.4 1077.87   727.7 1045.38   778.2 1033.76   799.0 1031.45   833.1 1024.75
   861.6 1022.18   942.2 1019.18   948.6 1019.56   963.6 1020.54   984.8 1027.49
  1067.8 1067.33  1171.9 1110.30  1191.5 1116.33  1272.2 1134.90  1294.3 1141.70
  1332.3 1162.46  1354.8 1171.94  1551.2 1225.80  1611.4 1241.00  1694.2 1266.67
#Mann= 3 , 0 , 0
       0     0.1       0   948.6   0.045       0   963.6     0.1       0
Bank Sta=   948.6,   963.6
Exp/Cntr=0.3,0.1

Type RM Length L Ch R = 1 ,25346.3,355.078,357.712,361.196
XS GIS Cut Line= 3
     1678934.543      237866.252     1678780.273      236908.506
     1678595.700      236088.060
#Sta/Elev= 30
       0 1173.97   120.1 1159.79   208.5 1159.15   241.0 1154.96   277.2 1146.75
   363.0 1131.79   463.1 1118.26   577.5 1096.23   599.5 1088.72   644.9 1085.73
   721.2 1068.62   756.4 1057.74   786.7 1044.76   828.6 1029.72   847.7 1025.33
   883.2 1020.17   917.9 1019.11   971.4 1019.79   986.4 1020.07  1006.1 1023.17
  1092.8 1069.23  1124.2 1081.14  1263.8 1120.41  1383.4 1149.63  1427.2 1162.95
  1456.4 1170.11  1477.1 1172.95  1704.4 1235.64  1759.7 1242.22  1811.0 1243.72
#Mann= 3 , 0 , 0
       0     0.1       0   971.4   0.045       0   986.4     0.1       0
Bank Sta=   971.4,   986.4
Exp/Cntr=0.3,0.1

Type RM Length L Ch R = 1 ,24988.6,564.389,575.637,586.729
XS GIS Cut Line= 3
     1679174.651      237578.324     1679124.571      236908.506
     1678892.550      236069.490
#Sta/Elev= 30
       0 1117.18    13.3 1117.07    52.1 1114.16   124.5 1101.21   254.2 1085.87
   387.7 1067.00   442.8 1061.12   468.2 1056.81   481.4 1053.26   556.2 1026.99
   570.5 1024.25   635.6 1017.47   638.7 1017.13   650.6 1017.64   662.1 1018.13
   695.8 1023.03   735.5 1042.16   803.0 1071.55   922.1 1104.15  1017.6 1133.05
  1077.7 1148.10  1115.1 1156.14  1214.6 1161.28  1284.0 1167.17  1311.8 1167.81
  1404.2 1156.08  1435.9 1153.25  1481.0 1146.88  1497.2 1146.39  1542.2 1153.15
#Mann= 3 , 0 , 0
       0     0.1       0   635.6   0.045       0   650.6     0.1       0
Bank Sta=   635.6,   650.6
Exp/Cntr=0.3,0.1

Type RM Length L Ch R = 1 ,24413,417.169,432.472,447.69
XS GIS Cut Line= 3
     1679499.758      237314.394     1679665.102      236932.983
     1680032.818      236096.466
#Sta/Elev= 30
       0 1056.75    94.6 1046.25   146.1 1043.85   249.8 1044.17   317.1 1039.24
   339.3 1038.74   364.2 1036.10   399.1 1026.69   429.0 1024.80   457.6 1015.55
   472.6 1014.60   473.5 1014.53   493.8 1016.25   513.4 1022.94   532.0 1027.52
   643.3 1082.44   662.0 1087.12   708.4 1095.47   720.6 1096.45   736.2 1096.88
   779.1 1092.02   792.1 1094.72   799.9 1098.25   831.0 1117.43   847.5 1124.90
  1009.6 1169.15  1102.4 1187.39  1191.1 1200.48  1223.5 1202.82  1329.5 1221.65
#Mann= 3 , 0 , 0
       0     0.1       0   457.6   0.045       0   472.6     0.1       0
Bank Sta=   457.6,   472.6
Exp/Cntr=0.3,0.1

Type RM Length L Ch R = 1 ,23980.5,521.502,499.723,478.185
XS GIS Cut Line= 3
     1679319.311      237454.587     1679853.545      237205.971
     1679997.894      237139.689
#Sta/Elev= 30
       0 1083.77    17.0 1081.09    31.2 1079.45    75.6 1075.98   120.2 1072.05
   139.5 1068.64   187.5 1060.88   233.0 1052.96   299.1 1044.34   338.7 1040.26
   372.1 1036.07   410.2 1032.17   455.6 1025.52   457.7 1025.29   523.2 1023.91
   536.3 1021.66   547.1 1017.67   553.2 1016.09   557.7 1015.73   571.3 1014.65
   572.7 1014.70   578.2 1014.88   588.6 1016.30   602.8 1021.23   611.4 1023.80
   614.8 1025.46   633.7 1030.49   667.0 1045.66   676.4 1048.47   748.1 1066.43
#Mann= 3 , 0 , 0
       0     0.1       0   557.7   0.045       0   572.7     0.1       0
Bank Sta=   557.7,   572.7
Exp/Cntr=0.3,0.1

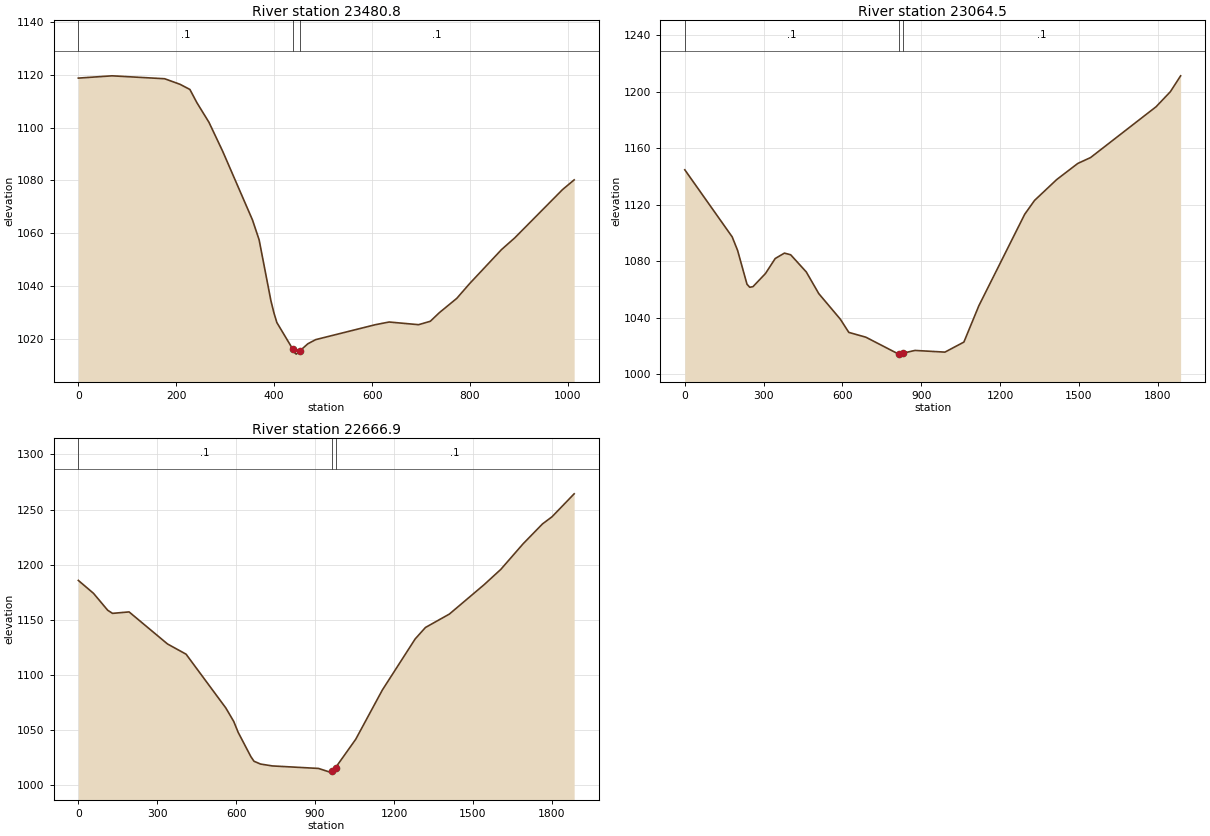
Type RM Length L Ch R = 1 ,23480.8,417.371,416.315,421.749
XS GIS Cut Line= 4
     1679894.549      238091.643     1680019.764      237396.822
     1680026.008      237171.426     1680029.161      237090.168
#Sta/Elev= 30
       0 1118.66    69.0 1119.52   176.3 1118.42   207.7 1116.32   227.9 1114.37
   242.3 1109.34   266.9 1101.95   294.9 1091.01   355.7 1065.10   369.3 1057.58
   393.4 1034.57   399.8 1029.83   405.5 1026.35   438.2 1016.24   441.7 1014.97
   445.1 1014.41   453.2 1015.74   468.8 1018.32   484.9 1019.89   606.6 1025.52
   634.8 1026.54   695.0 1025.53   719.0 1026.82   737.4 1030.06   773.1 1035.48
   799.0 1040.99   864.5 1053.91   891.4 1058.31   989.3 1076.60  1012.8 1080.22
#Mann= 3 , 0 , 0
       0     0.1       0   438.2   0.045       0   453.2     0.1       0
Bank Sta=   438.2,   453.2
Exp/Cntr=0.3,0.1

Type RM Length L Ch R = 1 ,23064.5,401.427,397.561,387.242
XS GIS Cut Line= 3
     1680384.611      238404.027     1680353.735      237429.178
     1680329.521      236517.770
#Sta/Elev= 30
       0 1144.76   180.4 1097.21   201.0 1087.61   236.7 1063.68   247.2 1061.52
   259.4 1061.93   307.0 1071.23   344.1 1081.88   379.2 1085.72   403.0 1084.53
   462.4 1072.36   509.9 1057.01   591.9 1038.91   624.3 1029.53   689.1 1026.13
   814.0 1014.13     815 1014.17     830 1014.79   875.9 1016.75   990.1 1015.55
  1062.2 1022.67  1119.1 1048.38  1293.8 1113.27  1331.1 1123.04  1415.3 1137.81
  1495.7 1149.26  1544.4 1153.43  1793.9 1189.47  1848.1 1200.11  1887.1 1211.35
#Mann= 3 , 0 , 0
       0     0.1       0     815   0.045       0     830     0.1       0
Bank Sta=     815,     830
Exp/Cntr=0.3,0.1

Type RM Length L Ch R = 1 ,22666.9,328.496,329.97,331.342
XS GIS Cut Line= 3
     1680722.156      238391.364     1680691.312      237417.535
     1680667.126      236507.147
#Sta/Elev= 30
       0 1185.80    57.7 1174.09   111.7 1158.76   130.1 1155.94   192.9 1157.27
   339.2 1128.19   409.6 1118.96   560.8 1070.20   590.8 1058.02   607.6 1048.18
   656.0 1026.10   667.8 1021.96   692.5 1019.42   737.6 1017.71   913.0 1015.43
   956.6 1012.09   962.7 1012.80   969.9 1013.30   977.7 1016.07  1054.5 1041.83
  1155.7 1086.46  1280.6 1132.78  1319.7 1143.16  1410.6 1155.30  1542.6 1181.92
  1606.1 1195.78  1690.9 1218.97  1764.5 1236.97  1800.8 1243.46  1885.0 1264.26
#Mann= 3 , 0 , 0
       0     0.1       0   962.7   0.045       0   977.7     0.1       0
Bank Sta=   962.7,   977.7
Exp/Cntr=0.3,0.1