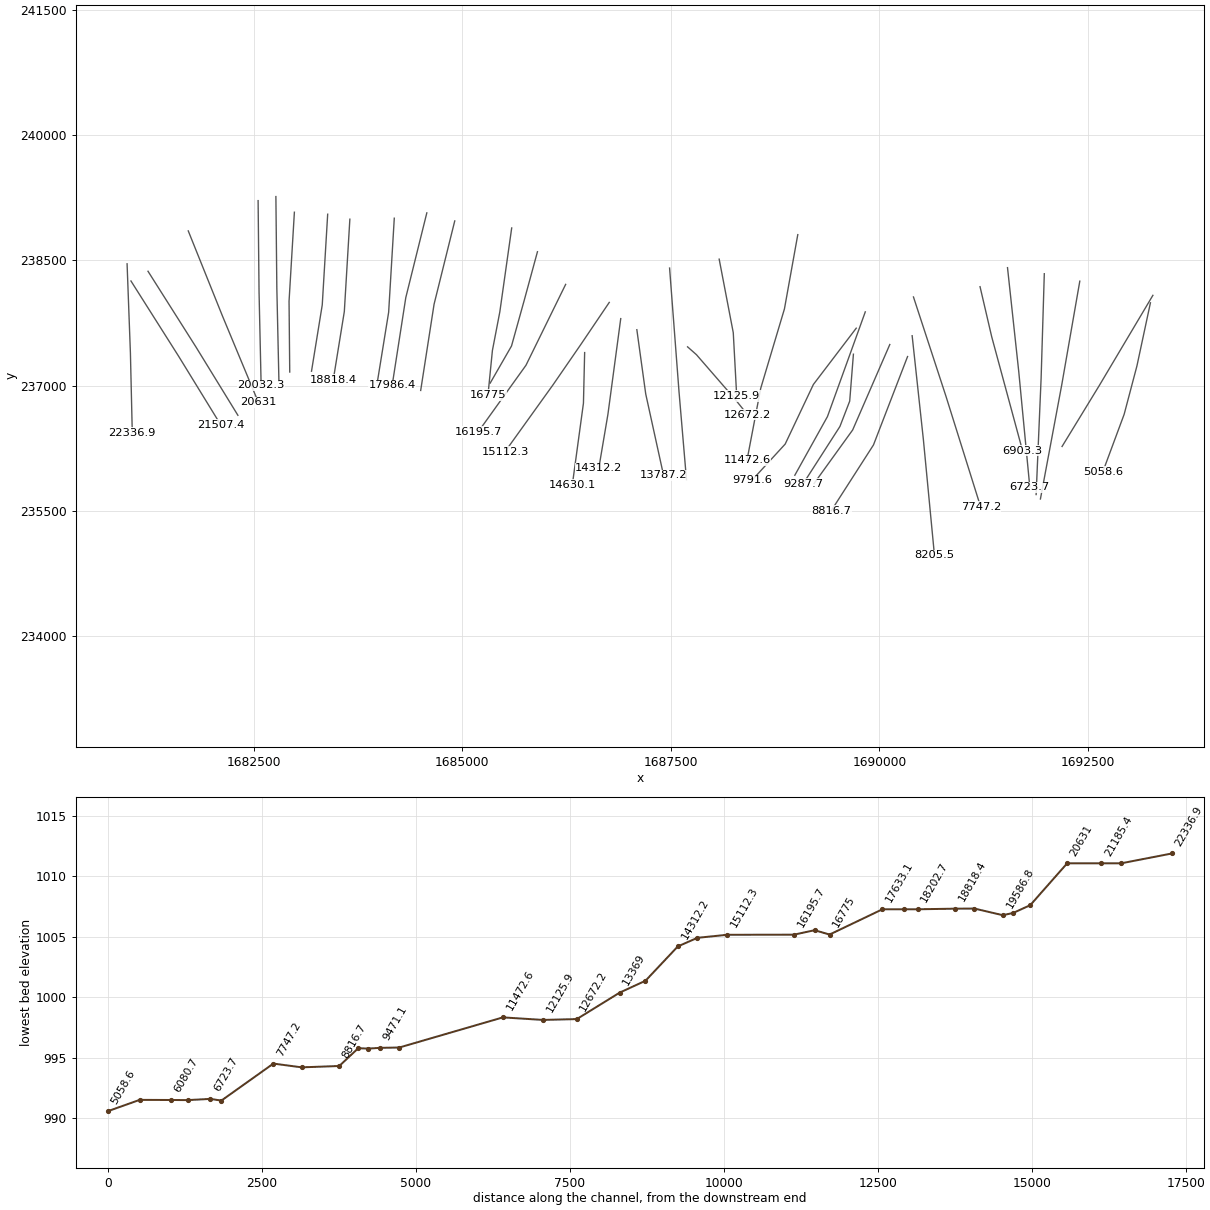
HEC-RAS study KinchloCr.prj: KinchloCr

--- KinchloCr.g01 (geometry) --- (continued)

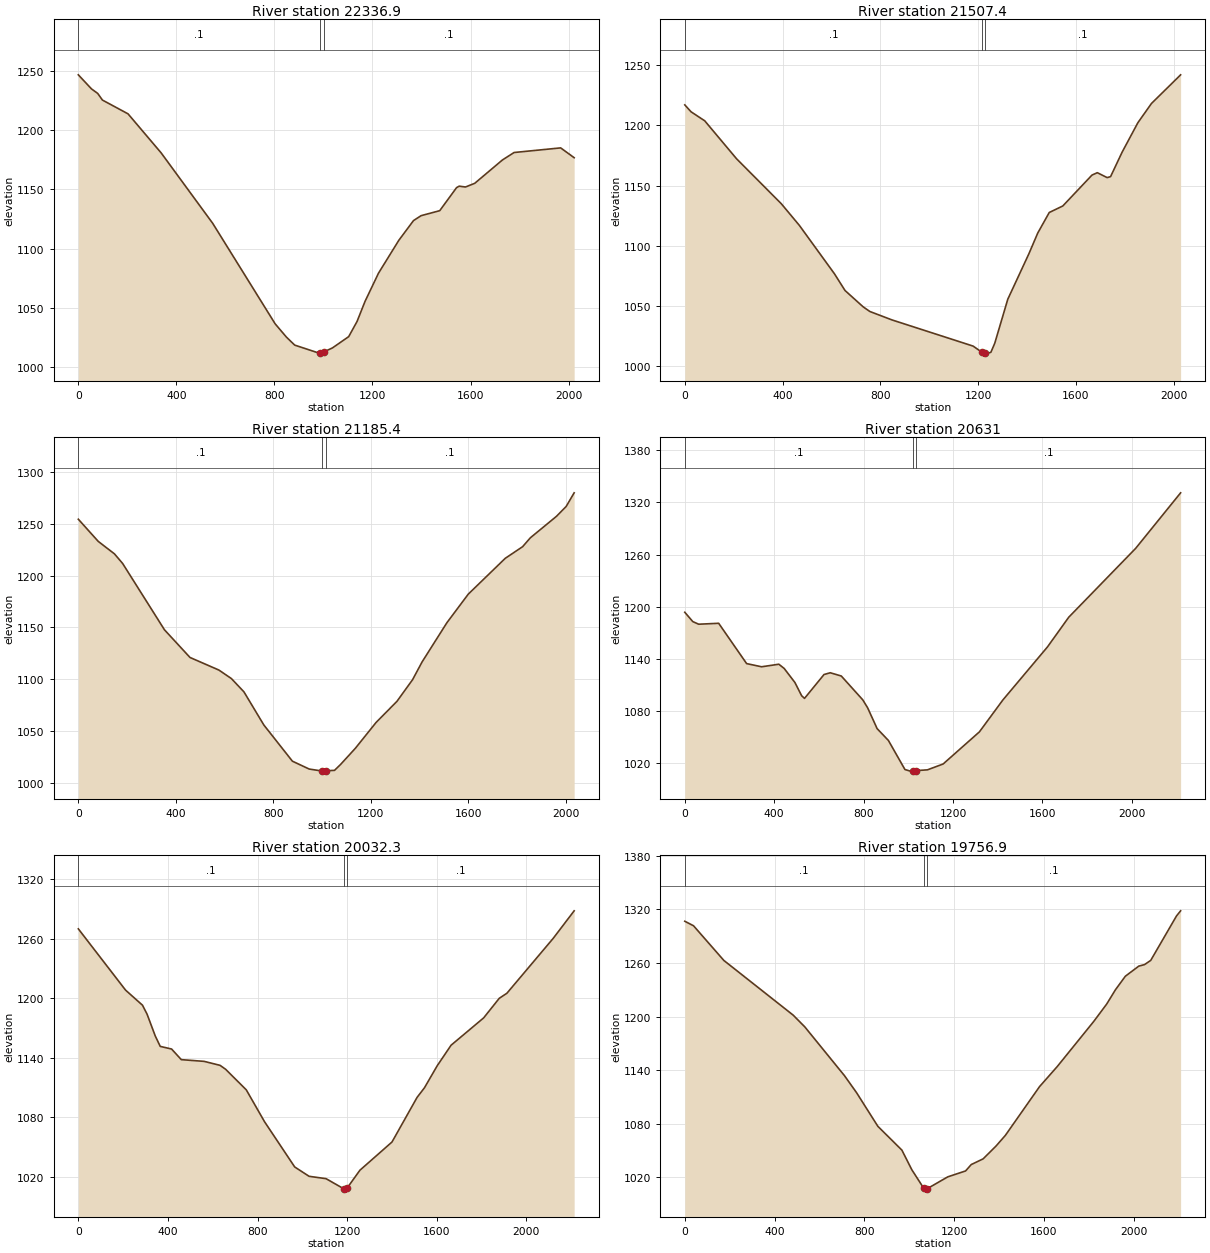
Type RM Length L Ch R = 1 ,22336.9,817.554,829.53,841.506
XS GIS Cut Line= 3
     1680980.029      238460.243     1681019.988      237391.232
     1681042.297      236438.413
#Sta/Elev= 30
       0 1246.58    53.5 1234.75    79.1 1230.89    98.3 1225.30   202.8 1213.68
   338.2 1180.67   548.2 1121.36   803.0 1036.60   849.0 1025.40   882.7 1018.67
   982.0 1011.90   986.3 1012.12  1001.3 1012.90  1036.7 1016.29  1103.0 1025.81
  1137.1 1038.60  1169.3 1055.37  1224.4 1079.25  1307.4 1107.01  1367.4 1123.67
  1398.3 1127.81  1474.4 1132.02  1543.0 1151.43  1553.6 1152.69  1579.4 1151.99
  1617.2 1155.10  1730.3 1174.80  1777.8 1181.07  1967.8 1184.97  2022.8 1176.70
#Mann= 3 , 0 , 0
       0     0.1       0   986.3   0.045       0  1001.3     0.1       0
Bank Sta=   986.3,  1001.3
Exp/Cntr=0.3,0.1

Type RM Length L Ch R = 1 ,21507.4,327.344,322.02,317.081
XS GIS Cut Line= 3
     1681026.494      238254.432     1681600.803      237348.602
     1682101.322      236534.250
#Sta/Elev= 30
       0 1216.86    25.7 1211.12    81.6 1203.65   211.8 1172.19   394.8 1134.92
   468.5 1117.02   612.4 1076.80   655.4 1063.01   729.5 1049.48   757.1 1045.59
   848.0 1038.58  1179.5 1016.91    1215 1011.86    1230 1011.26  1242.3 1011.08
  1252.2 1011.79  1268.1 1019.30  1321.3 1055.74  1407.8 1093.49  1443.9 1110.61
  1491.0 1127.66  1546.4 1133.06  1665.8 1158.67  1687.6 1160.66  1727.9 1156.57
  1741.9 1157.41  1788.8 1177.56  1853.4 1202.04  1909.1 1218.02  2028.4 1241.78
#Mann= 3 , 0 , 0
       0     0.1       0    1215   0.045       0    1230     0.1       0
Bank Sta=    1215,    1230
Exp/Cntr=0.3,0.1

Type RM Length L Ch R = 1 ,21185.4,552.686,554.359,555.646
XS GIS Cut Line= 3
     1681230.915      238370.789     1681806.719      237462.602
     1682308.699      236645.872
#Sta/Elev= 30
       0 1254.51    81.7 1233.09   148.2 1221.03   181.8 1211.74   353.5 1147.61
   458.1 1120.91   576.7 1108.74   627.9 1100.52   679.4 1087.68   760.9 1055.72
   878.1 1020.70   946.9 1013.11  1001.4 1011.09  1007.1 1011.08  1016.4 1011.42
  1050.9 1011.83  1075.3 1017.40  1136.4 1033.14  1221.4 1058.10  1307.1 1078.53
  1371.2 1099.46  1410.1 1116.57  1512.0 1154.51  1599.8 1182.15  1751.4 1216.74
  1822.6 1227.98  1854.3 1236.56  1961.5 1257.33  2001.2 1266.84  2034.0 1280.02
#Mann= 3 , 0 , 0
       0     0.1       0  1001.4   0.045       0  1016.4     0.1       0
Bank Sta=  1001.4,  1016.4
Exp/Cntr=0.3,0.1

Type RM Length L Ch R = 1 ,20631,609.744,598.673,587.601
XS GIS Cut Line= 3
     1681713.514      238854.290     1682123.323      237835.891
     1682554.128      236801.565
#Sta/Elev= 30
       0 1193.61    35.9 1182.88    62.1 1179.90   151.6 1180.96   276.6 1134.64
   343.6 1130.98   420.8 1133.93   444.7 1129.02   492.4 1113.02   522.8 1097.71
   535.6 1094.67   622.9 1122.10   650.8 1124.11   700.2 1120.36   796.1 1093.01
   817.9 1083.89   860.4 1059.93   910.9 1046.32   984.9 1012.92  1009.1 1011.08
  1020.5 1011.37  1035.4 1011.67  1085.4 1012.55  1155.7 1019.27  1318.0 1056.18
  1423.2 1092.91  1622.8 1153.89  1717.7 1187.93  2016.9 1267.01  2218.2 1330.87
#Mann= 3 , 0 , 0
       0     0.1       0  1020.5   0.045       0  1035.4     0.1       0
Bank Sta=  1020.5,  1035.4
Exp/Cntr=0.3,0.1

Type RM Length L Ch R = 1 ,20032.3,271.383,275.476,279.586
XS GIS Cut Line= 3
     1682551.175      239216.688     1682562.467      238121.400
     1682587.493      237003.639
#Sta/Elev= 30
       0 1269.85   210.9 1208.11   286.4 1192.93   306.9 1183.88   343.5 1161.89
   365.6 1151.44   416.3 1148.77   459.7 1138.07   561.9 1136.33   632.7 1132.33
   657.5 1128.37   749.7 1107.66   831.5 1075.44   966.0 1029.94  1030.1 1020.54
  1105.9 1018.15  1184.8 1007.99  1187.2 1007.62  1199.8 1008.66  1256.9 1026.63
  1400.2 1055.09  1512.4 1100.12  1545.2 1109.74  1602.1 1131.93  1664.0 1152.62
  1809.3 1180.12  1879.1 1199.88  1913.3 1204.99  2119.8 1260.25  2213.4 1288.01
#Mann= 3 , 0 , 0
       0     0.1       0  1184.8   0.045       0  1199.8     0.1       0
Bank Sta=  1184.8,  1199.8
Exp/Cntr=0.3,0.1

Type RM Length L Ch R = 1 ,19756.9,170.697,170.051,169.387
XS GIS Cut Line= 3
     1682764.391      239265.279     1682775.658      238172.406
     1682800.630      237057.060
#Sta/Elev= 30
       0 1306.82    38.9 1301.77   173.9 1262.97   482.9 1201.70   534.4 1188.63
   711.3 1133.98   765.4 1114.83   860.0 1077.29   967.0 1050.65  1011.2 1028.71
  1063.9 1008.14  1073.2 1006.98  1078.9 1007.33  1171.4 1020.71  1250.7 1027.33
  1276.0 1034.49  1329.0 1040.87  1386.2 1055.17  1428.0 1067.17  1580.2 1121.72
  1658.8 1144.11  1821.1 1194.52  1879.1 1214.06  1918.3 1230.13  1962.5 1245.31
  2022.3 1256.60  2047.9 1258.32  2075.5 1263.02  2190.4 1312.82  2208.6 1318.49
#Mann= 3 , 0 , 0
       0     0.1       0  1063.9   0.045       0  1078.9     0.1       0
Bank Sta=  1063.9,  1078.9
Exp/Cntr=0.3,0.1

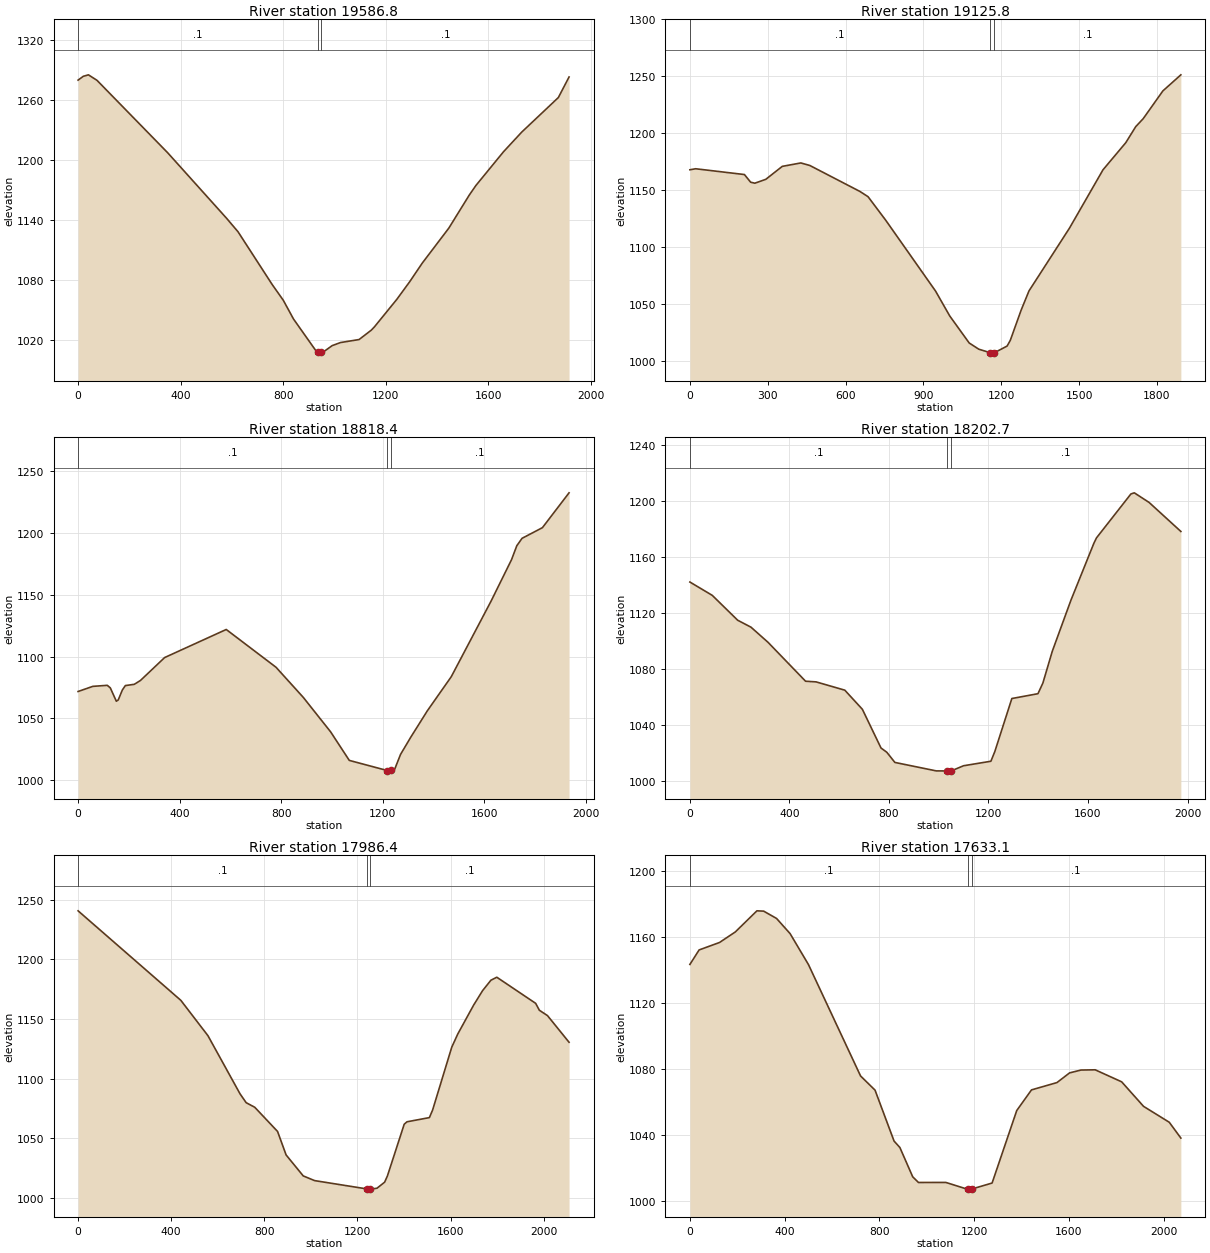
Type RM Length L Ch R = 1 ,19586.8,458.922,461.01,465.134
XS GIS Cut Line= 3
     1682986.153      239078.015     1682922.179      238011.785
     1682930.407      237164.091
#Sta/Elev= 30
       0 1280.24    20.1 1284.04    40.3 1285.55    73.9 1280.02   349.2 1207.60
   578.9 1142.03   624.2 1128.33   756.8 1075.75   800.6 1059.80   840.8 1040.90
   929.7 1008.59   934.7 1007.76   941.1 1006.79   949.7 1007.49   957.0 1007.94
   991.1 1014.25  1023.6 1017.36  1096.6 1020.41  1144.2 1029.81  1155.7 1032.88
  1243.5 1060.56  1294.2 1078.37  1343.0 1096.92  1446.7 1131.99  1526.6 1165.12
  1552.5 1174.73  1660.3 1208.54  1730.9 1228.10  1874.2 1262.81  1915.9 1283.39
#Mann= 3 , 0 , 0
       0     0.1       0   934.7   0.045       0   949.7     0.1       0
Bank Sta=   934.7,   949.7
Exp/Cntr=0.3,0.1

Type RM Length L Ch R = 1 ,19125.8,312.644,307.451,300.301
XS GIS Cut Line= 3
     1683385.435      239054.058     1683320.253      237967.680
     1683191.514      237173.790
#Sta/Elev= 30
       0 1168.16    22.0 1169.05   210.2 1163.98   234.0 1157.29   250.3 1156.38
   292.6 1159.78   356.1 1171.15   427.7 1174.15   462.3 1171.93   655.6 1149.13
   686.7 1144.55   754.1 1124.15   947.1 1061.72  1001.5 1039.99  1076.6 1016.25
  1113.5 1010.80  1158.4 1007.67  1163.0 1007.34  1173.4 1007.65  1222.7 1013.53
  1235.0 1018.51  1276.8 1045.00  1307.2 1061.93  1463.2 1116.97  1592.5 1168.15
  1680.3 1191.93  1718.6 1205.99  1747.3 1212.95  1823.3 1237.34  1892.6 1251.44
#Mann= 3 , 0 , 0
       0     0.1       0  1158.4   0.045       0  1173.4     0.1       0
Bank Sta=  1158.4,  1173.4
Exp/Cntr=0.3,0.1

Type RM Length L Ch R = 1 ,18818.4,614.394,615.624,616.558
XS GIS Cut Line= 3
     1683651.315      238994.527     1683584.923      237888.002
     1683452.954      237074.187
#Sta/Elev= 30
       0 1071.77    57.9 1075.93   114.9 1076.77   126.8 1074.73   150.6 1063.90
   158.0 1064.91   174.4 1073.03   186.1 1076.57   221.2 1077.58   245.8 1080.74
   340.9 1099.26   583.3 1121.96   779.2 1091.41   886.8 1066.97   994.2 1039.15
  1067.8 1016.01  1217.5 1007.80  1223.2 1007.33  1232.5 1008.00  1246.4 1008.82
  1269.5 1020.83  1309.6 1034.72  1375.4 1056.25  1469.3 1083.76  1625.8 1144.85
  1706.6 1178.48  1727.3 1189.75  1748.0 1195.74  1828.2 1204.37  1933.0 1232.56
#Mann= 3 , 0 , 0
       0     0.1       0  1217.5   0.045       0  1232.5     0.1       0
Bank Sta=  1217.5,  1232.5
Exp/Cntr=0.3,0.1

Type RM Length L Ch R = 1 ,18202.7,215.659,216.35,215.613
XS GIS Cut Line= 3
     1684183.999      239006.144     1684116.399      237879.471
     1683981.198      237045.733
#Sta/Elev= 30
       0 1142.10    90.0 1132.58   192.1 1114.86   245.5 1109.91   314.0 1099.12
   464.9 1071.38   507.1 1070.91   622.6 1065.00   693.2 1051.37   768.1 1023.76
   791.4 1020.74   823.9 1013.48   990.1 1007.45  1033.8 1007.40  1048.3 1007.28
  1048.8 1007.33  1099.8 1011.11  1209.8 1014.33  1225.5 1021.21  1294.0 1059.04
  1398.9 1062.48  1418.7 1070.07  1456.5 1092.73  1531.1 1128.97  1623.9 1169.84
  1634.2 1173.58  1772.6 1204.90  1786.2 1205.70  1845.6 1198.85  1973.3 1178.16
#Mann= 3 , 0 , 0
       0     0.1       0  1033.8   0.045       0  1048.8     0.1       0
Bank Sta=  1033.8,  1048.8
Exp/Cntr=0.3,0.1

Type RM Length L Ch R = 1 ,17986.4,355.974,353.313,352.079
XS GIS Cut Line= 3
     1684574.222      239070.188     1684322.061      238055.379
     1684158.718      237004.749
#Sta/Elev= 30
       0 1240.69   441.4 1165.61   557.7 1136.00   695.6 1087.21   722.0 1079.78
   758.9 1075.93   856.8 1055.66   893.5 1035.96   967.0 1018.38  1015.8 1014.43
  1239.7 1007.48  1254.7 1007.30  1256.6 1007.28  1283.9 1008.03  1316.7 1013.11
  1328.7 1018.34  1400.8 1061.70  1412.8 1063.75  1509.0 1067.27  1522.9 1073.67
  1605.1 1126.35  1631.0 1137.40  1698.7 1161.50  1737.3 1173.69  1773.3 1182.50
  1798.6 1185.00  1965.5 1163.09  1981.3 1157.32  2016.5 1152.77  2108.9 1130.46
#Mann= 3 , 0 , 0
       0     0.1       0  1239.7   0.045       0  1254.7     0.1       0
Bank Sta=  1239.7,  1254.7
Exp/Cntr=0.3,0.1

Type RM Length L Ch R = 1 ,17633.1,858.812,858.068,857.324
XS GIS Cut Line= 3
     1684909.057      238973.729     1684661.205      237976.266
     1684500.608      236943.299
#Sta/Elev= 30
       0 1143.55    38.9 1152.33   125.1 1156.85   191.7 1163.24   283.0 1176.05
   311.5 1175.86   365.9 1171.43   423.1 1162.23   500.5 1143.50   720.7 1075.90
   781.8 1067.31   862.1 1036.43   886.7 1032.52   940.9 1014.75   965.3 1011.30
  1080.8 1011.34  1170.7 1007.28  1174.6 1007.28  1189.6 1007.32  1276.1 1010.97
  1380.1 1054.92  1442.5 1067.46  1549.9 1071.89  1603.3 1077.77  1651.3 1079.49
  1711.4 1079.64  1823.3 1072.34  1915.6 1057.48  2024.2 1047.83  2073.2 1038.24
#Mann= 3 , 0 , 0
       0     0.1       0  1174.6   0.045       0  1189.6     0.1       0
Bank Sta=  1174.6,  1189.6
Exp/Cntr=0.3,0.1

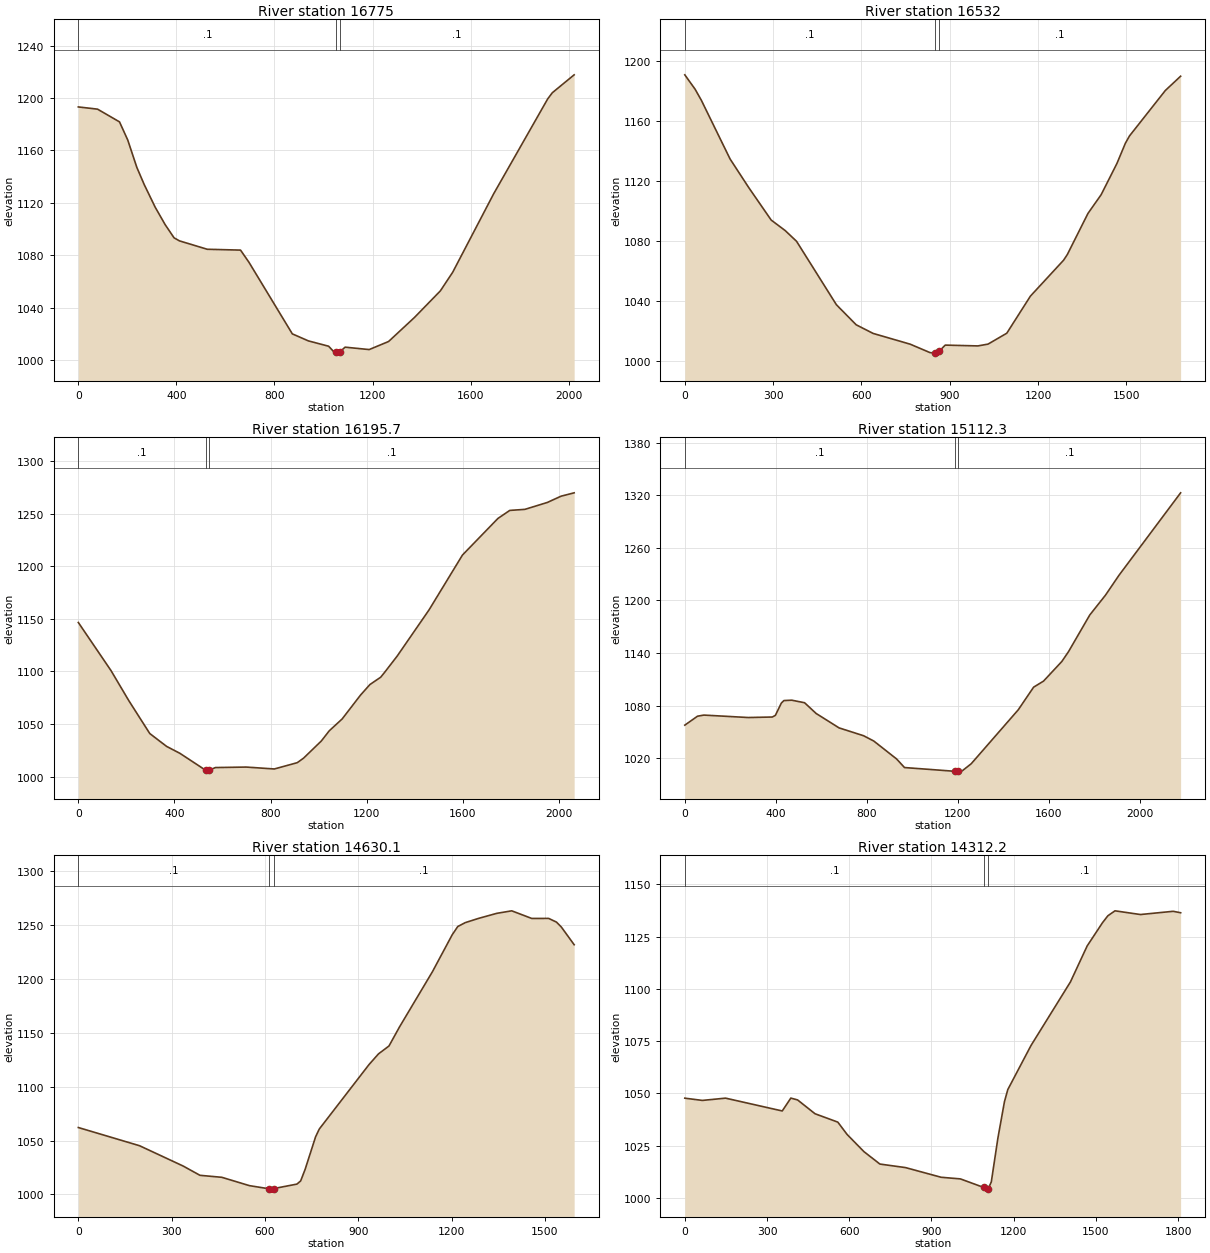
Type RM Length L Ch R = 1 ,16775,244.966,243.031,241.096
XS GIS Cut Line= 4
     1685591.889      238889.426     1685449.593      237884.463
     1685360.658      237422.002     1685307.297      236888.393
#Sta/Elev= 30
       0 1193.20    78.3 1191.51   167.9 1181.79   201.5 1167.95   238.8 1146.94
   268.7 1133.93   313.4 1116.65   354.2 1103.29   390.5 1093.23   412.6 1090.91
   525.7 1084.51   661.5 1083.86   695.7 1074.63   872.8 1019.89   938.2 1014.54
  1020.8 1010.46  1040.8 1006.47    1052 1005.76  1061.2 1005.19    1067 1006.28
  1088.2 1009.74  1186.2 1007.91  1265.3 1014.06  1370.9 1032.42  1476.6 1052.75
  1526.9 1066.97  1694.0 1126.89  1914.4 1199.37  1933.3 1204.07  2022.2 1217.72
#Mann= 3 , 0 , 0
       0     0.1       0    1052   0.045       0    1067     0.1       0
Bank Sta=    1052,    1067
Exp/Cntr=0.3,0.1

Type RM Length L Ch R = 1 ,16532,340.385,336.241,332.097
XS GIS Cut Line= 4
     1685900.829      238604.835     1685740.747      238017.865
     1685589.557      237475.363     1685333.898      237031.322
#Sta/Elev= 30
       0 1190.93    34.9 1181.38    56.1 1174.02   153.8 1134.87   217.1 1115.85
   293.4 1094.19   340.7 1087.23   379.5 1080.06   514.9 1037.79   582.0 1024.44
   639.4 1018.69   765.4 1011.52   832.6 1005.91   848.3 1005.62   859.8 1005.55
   863.3 1006.66   884.5 1010.89   995.4 1010.35  1029.8 1011.54  1093.6 1018.81
  1173.9 1043.53  1286.4 1067.42  1299.3 1071.27  1369.3 1098.60  1414.0 1111.06
  1467.7 1131.90  1496.3 1145.32  1510.3 1150.21  1632.1 1180.50  1684.0 1190.01
#Mann= 3 , 0 , 0
       0     0.1       0   848.3   0.045       0   863.3     0.1       0
Bank Sta=   848.3,   863.3
Exp/Cntr=0.3,0.1

Type RM Length L Ch R = 1 ,16195.7,1087.542,1083.441,1078.282
XS GIS Cut Line= 3
     1686238.781      238213.521     1685762.770      237244.330
     1685188.650      236445.424
#Sta/Elev= 30
       0 1146.59   136.0 1100.83   210.3 1072.16   297.4 1040.94   367.3 1028.72
   423.2 1022.06     530 1006.00   534.2 1005.18     545 1006.19   570.7 1008.58
   698.8 1009.04   815.7 1007.23   911.1 1013.21   937.3 1017.50  1011.4 1033.87
  1044.4 1043.55  1098.0 1054.81  1174.4 1077.50  1213.7 1087.58  1258.4 1094.53
  1273.4 1098.75  1327.0 1114.62  1459.6 1158.55  1598.8 1210.78  1746.4 1245.58
  1795.7 1253.22  1858.3 1254.20  1952.1 1260.80  2009.1 1266.75  2063.6 1269.95
#Mann= 3 , 0 , 0
       0     0.1       0     530   0.045       0     545     0.1       0
Bank Sta=     530,     545
Exp/Cntr=0.3,0.1

Type RM Length L Ch R = 1 ,15112.3,470.454,482.154,493.199
XS GIS Cut Line= 4
     1686761.746      237997.743     1686421.282      237494.505
     1686087.574      237010.872     1685513.474      236211.995
#Sta/Elev= 30
       0 1057.61    55.8 1067.81    83.7 1069.09   278.9 1066.31   384.6 1066.88
   398.0 1068.77   424.2 1082.77   435.5 1085.64   470.0 1086.08   526.4 1083.17
   577.1 1070.94   678.1 1054.47   785.3 1045.58   830.5 1039.50   930.6 1019.08
   965.6 1009.25  1176.8 1005.17  1187.7 1005.17  1202.7 1005.17  1218.1 1005.29
  1258.7 1013.60  1465.5 1075.16  1532.9 1100.94  1576.5 1107.85  1656.9 1130.24
  1686.2 1141.42  1779.6 1183.24  1848.7 1205.88  1908.0 1228.54  2178.9 1322.60
#Mann= 3 , 0 , 0
       0     0.1       0  1187.7   0.045       0  1202.7     0.1       0
Bank Sta=  1187.7,  1202.7
Exp/Cntr=0.3,0.1

Type RM Length L Ch R = 1 ,14630.1,318.844,317.98,318.246
XS GIS Cut Line= 3
     1686466.663      237396.954     1686452.225      236790.565
     1686318.823      235812.282
#Sta/Elev= 30
       0 1062.14   196.7 1045.24   336.9 1026.38   391.1 1017.74   461.2 1015.90
   550.0 1008.16   613.1 1005.23   618.9 1004.92   628.1 1005.44   702.7 1009.59
   714.7 1012.54   728.9 1023.14   762.7 1053.50   774.6 1060.74   934.2 1120.51
   964.9 1130.53   998.6 1137.85  1032.2 1155.43  1138.4 1206.89  1201.8 1241.11
  1219.7 1248.81  1243.9 1252.45  1286.3 1256.35  1345.2 1261.06  1393.3 1263.40
  1457.6 1256.32  1511.9 1256.36  1537.0 1252.94  1552.7 1248.34  1593.9 1231.94
#Mann= 3 , 0 , 0
       0     0.1       0   613.1   0.045       0   628.1     0.1       0
Bank Sta=   613.1,   628.1
Exp/Cntr=0.3,0.1

Type RM Length L Ch R = 1 ,14312.2,519.083,524.985,531.927
XS GIS Cut Line= 3
     1686899.465      237803.683     1686745.710      236657.163
     1686636.546      236013.329
#Sta/Elev= 30
       0 1047.72    64.2 1046.64   148.7 1047.73   355.5 1041.60   386.9 1047.76
   411.6 1046.87   475.2 1040.26   558.3 1036.26   592.0 1030.39   653.7 1022.13
   711.9 1016.20   805.3 1014.51   935.3 1009.88  1005.6 1009.10  1090.8 1005.00
  1105.8 1004.22  1106.4 1004.21  1118.3 1007.67  1142.3 1028.59  1166.3 1046.07
  1178.4 1051.81  1263.1 1072.90  1406.9 1103.30  1468.1 1120.55  1523.9 1131.63
  1543.5 1134.95  1569.5 1137.33  1662.4 1135.56  1781.9 1137.10  1809.0 1136.41
#Mann= 3 , 0 , 0
       0     0.1       0  1090.8   0.045       0  1105.8     0.1       0
Bank Sta=  1090.8,  1105.8
Exp/Cntr=0.3,0.1

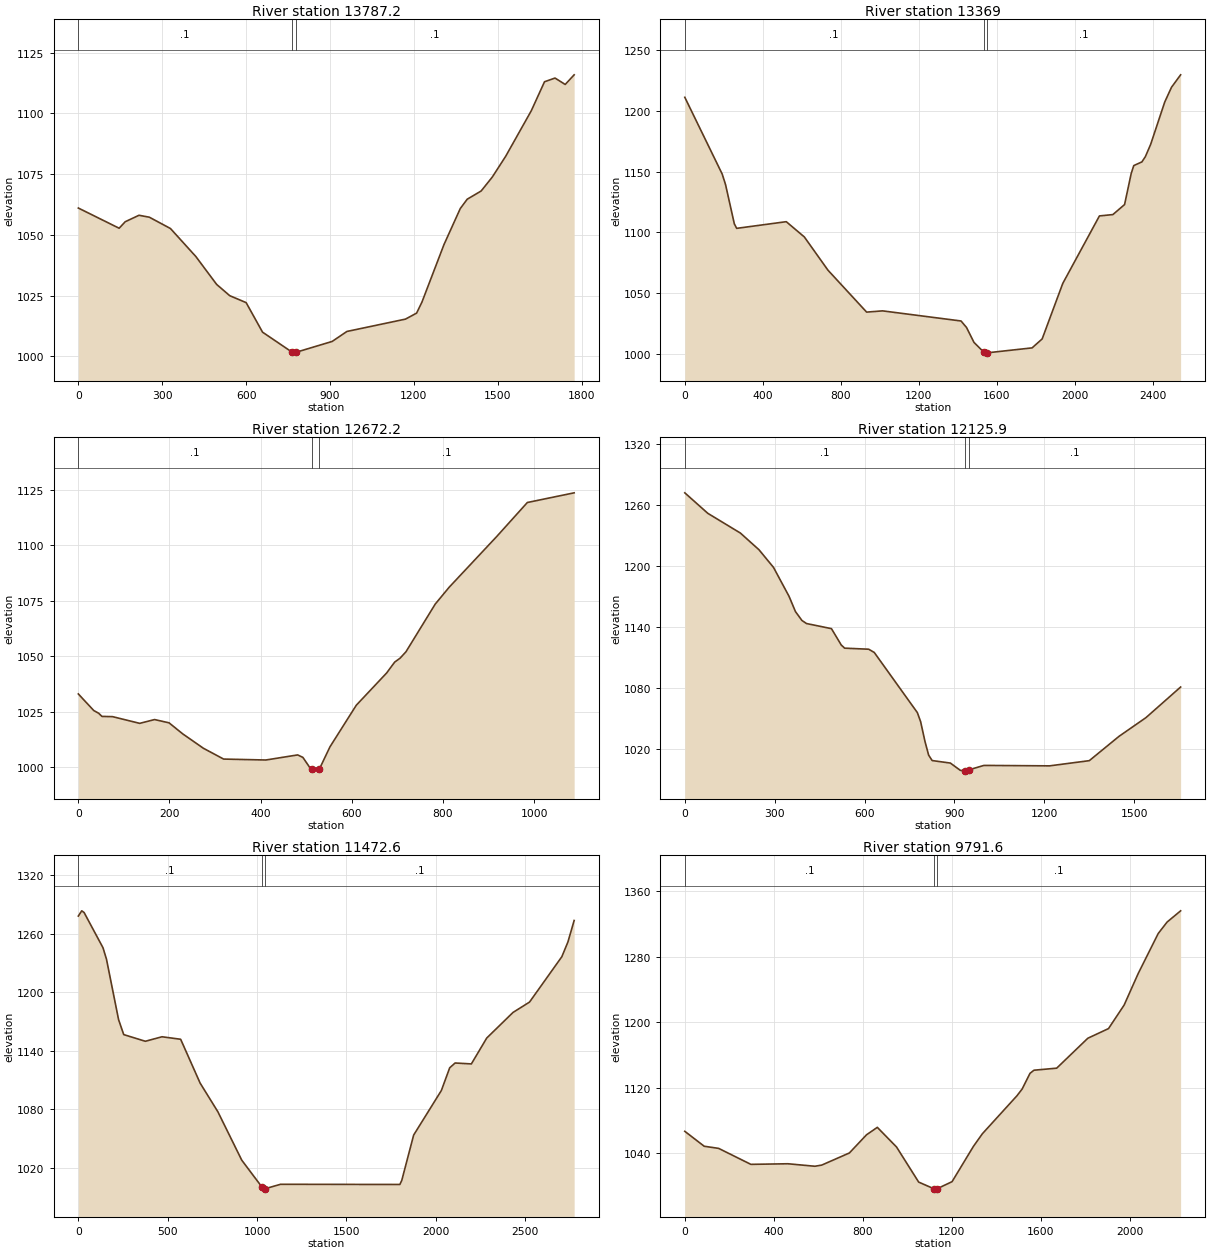
Type RM Length L Ch R = 1 ,13787.2,415.917,418.19,420.095
XS GIS Cut Line= 3
     1687092.556      237671.019     1687199.112      236900.882
     1687412.721      235927.897
#Sta/Elev= 30
       0 1061.05   146.0 1052.74   167.7 1055.41   216.9 1058.07   253.9 1057.28
   329.5 1052.63   420.4 1041.10   494.7 1029.64   541.6 1025.00   600.3 1022.14
   658.9 1010.00   763.9 1001.82   769.3 1001.37   778.9 1001.72   908.0 1006.18
   960.7 1010.28  1170.3 1015.36  1210.0 1017.83  1229.0 1022.32  1308.0 1046.03
  1366.3 1060.85  1391.1 1064.68  1441.0 1068.07  1480.9 1073.81  1528.5 1082.30
  1620.1 1101.03  1667.6 1112.99  1705.1 1114.51  1741.6 1111.88  1773.6 1115.84
#Mann= 3 , 0 , 0
       0     0.1       0   763.9   0.045       0   778.9     0.1       0
Bank Sta=   763.9,   778.9
Exp/Cntr=0.3,0.1

Type RM Length L Ch R = 1 ,13369,689.789,696.732,707.057
XS GIS Cut Line= 3
     1687485.152      238409.007     1687597.819      236933.065
     1687687.953      235873.993
#Sta/Elev= 30
       0 1211.25   191.8 1148.00   209.1 1139.23   254.1 1106.95   266.1 1103.23
   520.4 1108.72   613.1 1096.15   734.1 1068.80   932.6 1034.19  1014.2 1035.22
  1416.9 1026.88  1444.9 1021.55  1483.3 1009.22  1532.5 1001.38  1542.3 1000.39
  1547.5 1000.58  1781.3 1004.71  1833.0 1012.11  1938.7 1057.87  2126.7 1113.47
  2195.5 1114.57  2255.6 1122.84  2289.6 1148.41  2302.8 1154.96  2344.5 1157.99
  2362.3 1162.34  2389.4 1172.43  2461.6 1207.34  2496.4 1219.52  2543.1 1229.76
#Mann= 3 , 0 , 0
       0     0.1       0  1532.5   0.045       0  1547.5     0.1       0
Bank Sta=  1532.5,  1547.5
Exp/Cntr=0.3,0.1

Type RM Length L Ch R = 1 ,12672.2,580.278,546.395,511.029
XS GIS Cut Line= 4
     1687700.743      237465.645     1687807.162      237371.745
     1688264.141      236845.907     1688420.640      236651.847
#Sta/Elev= 30
       0 1032.97    33.9 1025.48    44.6 1024.28    51.8 1022.85    75.1 1022.74
   134.7 1019.72   167.3 1021.43   199.1 1019.95   228.8 1015.02   274.4 1008.50
   318.8 1003.63   411.4 1003.21   481.2 1005.50   492.7 1004.39   509.9  999.20
   512.1  999.02   521.4  998.20   527.1  999.23   530.5  999.82   552.1 1009.14
   609.9 1027.89   676.5 1042.42   694.1 1047.31   706.0 1049.09   718.8 1051.94
   783.1 1073.45   813.8 1081.06   917.9 1103.86   985.2 1119.20  1087.9 1123.56
#Mann= 3 , 0 , 0
       0     0.1       0   512.1   0.045       0   527.1     0.1       0
Bank Sta=   512.1,   527.1
Exp/Cntr=0.3,0.1

Type RM Length L Ch R = 1 ,12125.9,641.371,653.229,666.569
XS GIS Cut Line= 3
     1688079.732      238515.900     1688248.708      237635.445
     1688289.896      236877.586
#Sta/Elev= 30
       0 1272.32    76.7 1252.15   185.5 1232.71   247.8 1216.22   296.2 1198.84
   348.0 1170.41   369.5 1155.31   391.1 1146.57   406.4 1143.54   489.7 1138.50
   522.4 1122.39   533.8 1119.28   614.0 1118.24   632.6 1115.05   776.5 1055.78
   787.5 1046.78   802.1 1027.17   814.2 1013.87   825.9 1008.55   886.7 1006.07
   919.5  998.99   934.5  998.14   934.8  998.13   949.5  999.46   998.5 1003.76
  1218.1 1003.32  1350.6 1008.44  1449.8 1032.40  1539.8 1050.84  1655.5 1080.99
#Mann= 3 , 0 , 0
       0     0.1       0   934.5   0.045       0   949.5     0.1       0
Bank Sta=   934.5,   949.5
Exp/Cntr=0.3,0.1

Type RM Length L Ch R = 1 ,11472.6,1684.383,1680.989,1677.596
XS GIS Cut Line= 4
     1689022.441      238809.385     1688862.358      237920.037
     1688577.767      236968.434     1688412.987      236106.077
#Sta/Elev= 30
       0 1278.38    19.1 1283.74    32.3 1282.00   138.0 1245.89   157.6 1234.12
   225.3 1172.12   254.1 1156.80   375.1 1149.97   468.4 1154.59   572.7 1152.02
   681.5 1107.12   780.9 1077.69   914.5 1028.05  1028.2 1000.34  1039.2  998.34
  1043.2  998.64  1131.8 1003.30  1799.2 1003.11  1810.0 1007.26  1876.6 1053.78
  2031.7 1099.49  2078.3 1122.76  2108.7 1127.69  2199.5 1126.74  2285.6 1153.29
  2432.5 1179.51  2525.1 1190.17  2706.0 1236.74  2739.9 1251.81  2774.8 1273.83
#Mann= 3 , 0 , 0
       0     0.1       0  1028.2   0.045       0  1043.2     0.1       0
Bank Sta=  1028.2,  1043.2
Exp/Cntr=0.3,0.1

Type RM Length L Ch R = 1 ,9791.6,318.343,320.534,319.576
XS GIS Cut Line= 4
     1689723.342      237689.126     1689209.398      237014.926
     1688871.359      236301.288     1688471.045      235865.643
#Sta/Elev= 30
       0 1066.49    87.2 1048.24   152.2 1045.63   297.0 1026.11   463.3 1026.84
   584.8 1023.80   615.5 1025.20   739.9 1040.02   816.8 1062.20   865.5 1071.33
   951.9 1047.32  1051.4 1004.45  1120.9  996.18  1128.8  995.85  1135.9  996.53
  1201.5 1004.96  1297.6 1048.12  1337.9 1063.55  1493.8 1110.08  1516.8 1118.27
  1551.9 1137.32  1569.7 1141.14  1671.8 1143.63  1811.8 1180.19  1904.8 1191.98
  1975.0 1220.71  2037.5 1258.80  2128.2 1308.11  2167.9 1322.06  2229.0 1335.87
#Mann= 3 , 0 , 0
       0     0.1       0  1120.9   0.045       0  1135.9     0.1       0
Bank Sta=  1120.9,  1135.9
Exp/Cntr=0.3,0.1

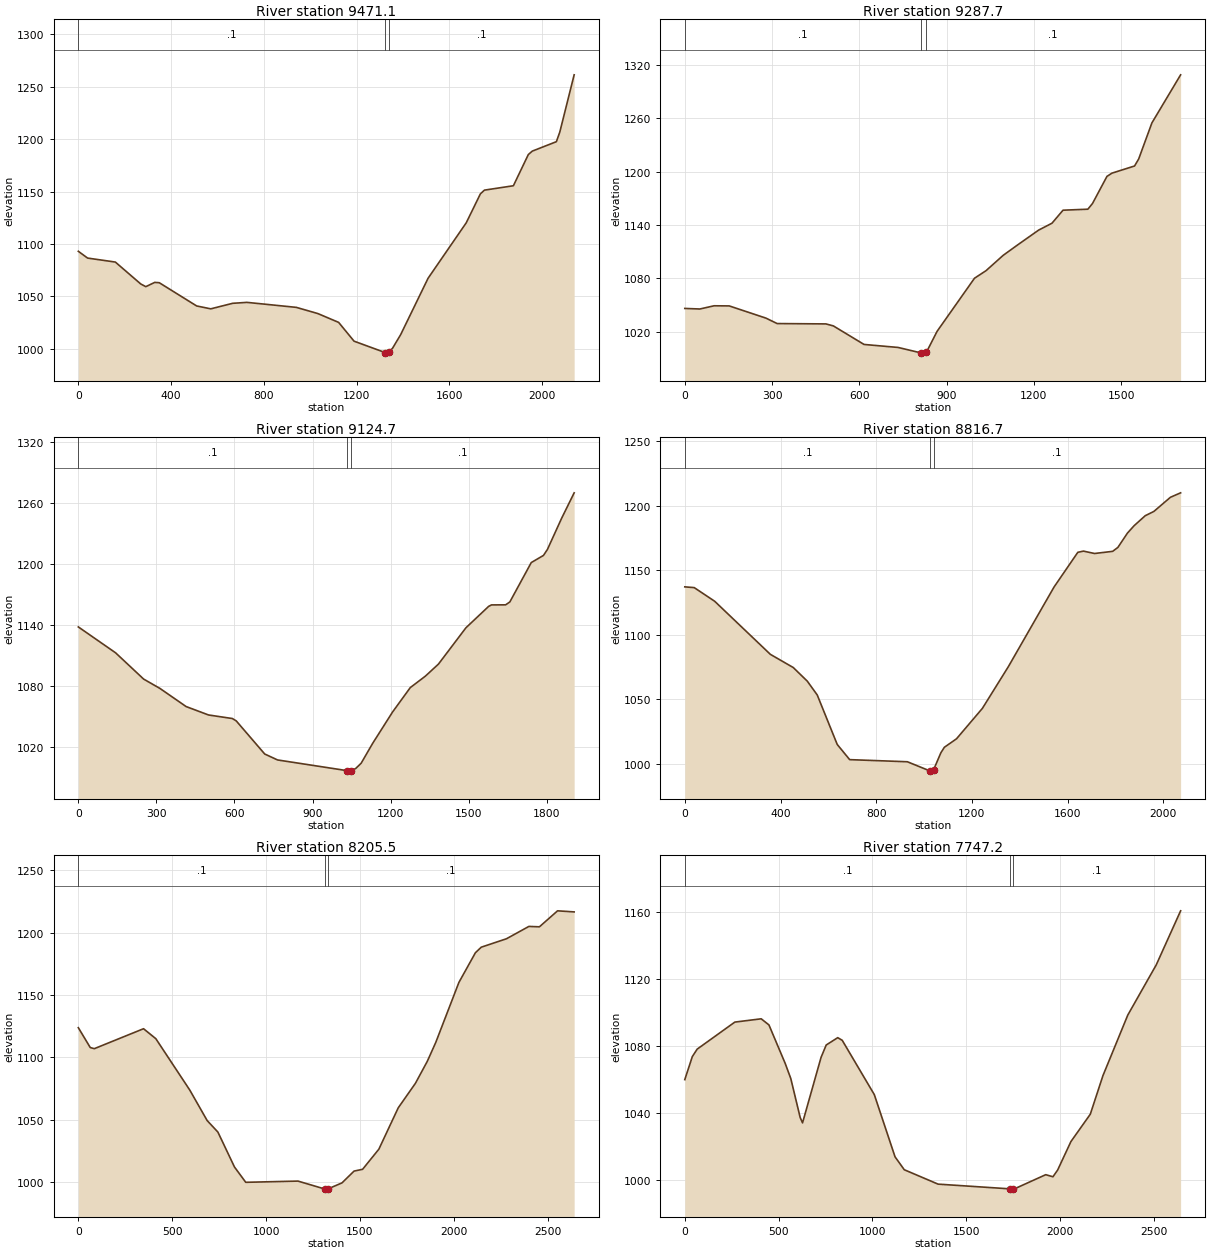
Type RM Length L Ch R = 1 ,9471.1,183.989,183.362,185.883
XS GIS Cut Line= 3
     1689831.747      237884.463     1689378.180      236630.482
     1688986.867      235927.897
#Sta/Elev= 30
       0 1093.00    39.9 1086.52   159.6 1082.72   269.1 1061.82   290.9 1059.25
   329.5 1063.33   349.0 1063.00   510.2 1040.83   571.0 1038.08   665.5 1043.36
   727.2 1044.25   939.9 1039.48  1032.4 1033.59  1122.3 1025.15  1188.8 1007.22
    1323  996.35  1330.1  995.82    1338  996.86  1354.5 1000.41  1389.7 1013.45
  1507.9 1067.26  1672.4 1120.16  1733.5 1147.82  1750.9 1151.36  1875.7 1155.54
  1940.2 1185.34  1957.3 1188.59  2061.1 1197.60  2075.7 1206.68  2137.7 1261.39
#Mann= 3 , 0 , 0
       0     0.1       0    1323   0.045       0    1338     0.1       0
Bank Sta=    1323,    1338
Exp/Cntr=0.3,0.1

Type RM Length L Ch R = 1 ,9287.7,163.787,163.003,162.219
XS GIS Cut Line= 4
     1689689.451      237377.534     1689644.869      236815.265
     1689527.715      236511.891     1689086.741      235825.932
#Sta/Elev= 30
       0 1046.04    51.5 1045.38   100.8 1049.00   152.7 1048.86   279.0 1035.13
   317.5 1029.01   485.1 1028.62   510.5 1026.42   616.3 1005.52   733.4 1002.14
   812.7  995.96   815.2  995.76   827.7  997.20   832.7  998.02   867.4 1020.27
   996.0 1079.98  1035.7 1088.50  1094.7 1105.75  1142.1 1116.95  1216.5 1134.11
  1262.4 1141.87  1300.4 1156.51  1385.8 1157.64  1401.9 1164.13  1451.4 1194.53
  1468.6 1198.17  1546.3 1206.23  1560.5 1214.10  1606.0 1254.71  1704.7 1308.76
#Mann= 3 , 0 , 0
       0     0.1       0   812.7   0.045       0   827.7     0.1       0
Bank Sta=   812.7,   827.7
Exp/Cntr=0.3,0.1

Type RM Length L Ch R = 1 ,9124.7,307.064,308.055,309.045
XS GIS Cut Line= 3
     1690125.752      237493.505     1689680.558      236470.400
     1689218.097      235830.069
#Sta/Elev= 30
       0 1137.76   143.1 1112.29   251.0 1086.41   313.8 1077.19   414.2 1059.37
   500.5 1051.07   591.8 1047.58   606.8 1045.27   716.3 1012.65   765.7 1006.79
  1031.9  996.30  1042.8  995.79  1046.9  996.14  1065.7  998.31  1087.0 1003.56
  1130.9 1023.00  1207.7 1053.99  1275.7 1078.00  1333.7 1089.28  1384.2 1101.20
  1489.6 1136.89  1577.1 1158.02  1588.0 1159.43  1642.3 1159.50  1658.5 1162.39
  1740.8 1201.13  1787.6 1208.14  1802.9 1214.06  1857.5 1244.75  1905.6 1269.78
#Mann= 3 , 0 , 0
       0     0.1       0  1031.9   0.045       0  1046.9     0.1       0
Bank Sta=  1031.9,  1046.9
Exp/Cntr=0.3,0.1

Type RM Length L Ch R = 1 ,8816.7,599.9,611.175,622.45
XS GIS Cut Line= 3
     1690338.812      237349.407     1689930.033      236290.862
     1689423.030      235502.191
#Sta/Elev= 30
       0 1137.08    39.5 1136.48   124.9 1125.92   357.6 1084.80   453.3 1074.58
   511.8 1064.06   553.5 1053.33   637.1 1014.98   689.1 1003.22   930.3 1001.58
  1024.7  994.45  1032.1  994.32  1039.7  995.29  1070.3 1008.54  1084.8 1012.78
  1135.7 1019.38  1243.8 1042.94  1352.2 1075.21  1543.2 1136.93  1642.6 1163.83
  1665.9 1164.78  1712.6 1162.93  1788.2 1164.59  1810.1 1167.64  1849.9 1178.70
  1878.0 1184.47  1924.3 1192.19  1960.5 1195.51  2029.7 1206.48  2072.3 1209.93
#Mann= 3 , 0 , 0
       0     0.1       0  1024.7   0.045       0  1039.7     0.1       0
Bank Sta=  1024.7,  1039.7
Exp/Cntr=0.3,0.1

Type RM Length L Ch R = 1 ,8205.5,453.8,458.283,462.767
XS GIS Cut Line= 3
     1690393.677      237599.022     1690528.327      236356.025
     1690661.091      234971.030
#Sta/Elev= 30
       0 1123.77    63.5 1107.84    85.0 1106.92   347.4 1122.93   412.8 1114.96
   593.8 1073.70   686.3 1049.25   743.6 1039.99   832.0 1011.95   892.0  999.68
  1170.2 1000.66  1314.3  994.25  1325.2  994.21  1329.3  994.34  1404.7  999.22
  1469.0 1008.68  1514.5 1010.13  1601.2 1026.28  1704.3 1059.43  1795.8 1079.10
  1859.1 1096.74  1904.3 1111.94  2027.7 1160.13  2115.4 1183.88  2146.5 1188.36
  2281.1 1195.14  2400.4 1205.03  2456.6 1204.72  2553.2 1217.55  2641.6 1216.68
#Mann= 3 , 0 , 0
       0     0.1       0  1314.3   0.045       0  1329.3     0.1       0
Bank Sta=  1314.3,  1329.3
Exp/Cntr=0.3,0.1

Type RM Length L Ch R = 1 ,7747.2,845.328,843.906,841.979
XS GIS Cut Line= 3
     1690409.460      238063.069     1690798.742      236874.949
     1691215.602      235547.520
#Sta/Elev= 30
       0 1059.87    40.1 1073.62    65.9 1078.06   266.6 1094.20   407.0 1096.16
   448.3 1092.51   534.9 1069.55   564.8 1060.48   614.8 1037.23   627.3 1034.06
   726.1 1073.18   753.4 1080.52   814.7 1084.90   838.8 1083.33  1009.9 1050.87
  1120.1 1013.80  1169.3 1006.09  1349.4  997.50  1733.7  994.67  1748.7  994.64
  1753.0  994.52  1923.0 1003.14  1961.3 1001.89  1986.2 1005.86  2057.2 1022.91
  2160.4 1039.23  2227.6 1062.20  2360.2 1098.41  2511.8 1128.35  2641.6 1160.60
#Mann= 3 , 0 , 0
       0     0.1       0  1733.7   0.045       0  1748.7     0.1       0
Bank Sta=  1733.7,  1748.7
Exp/Cntr=0.3,0.1

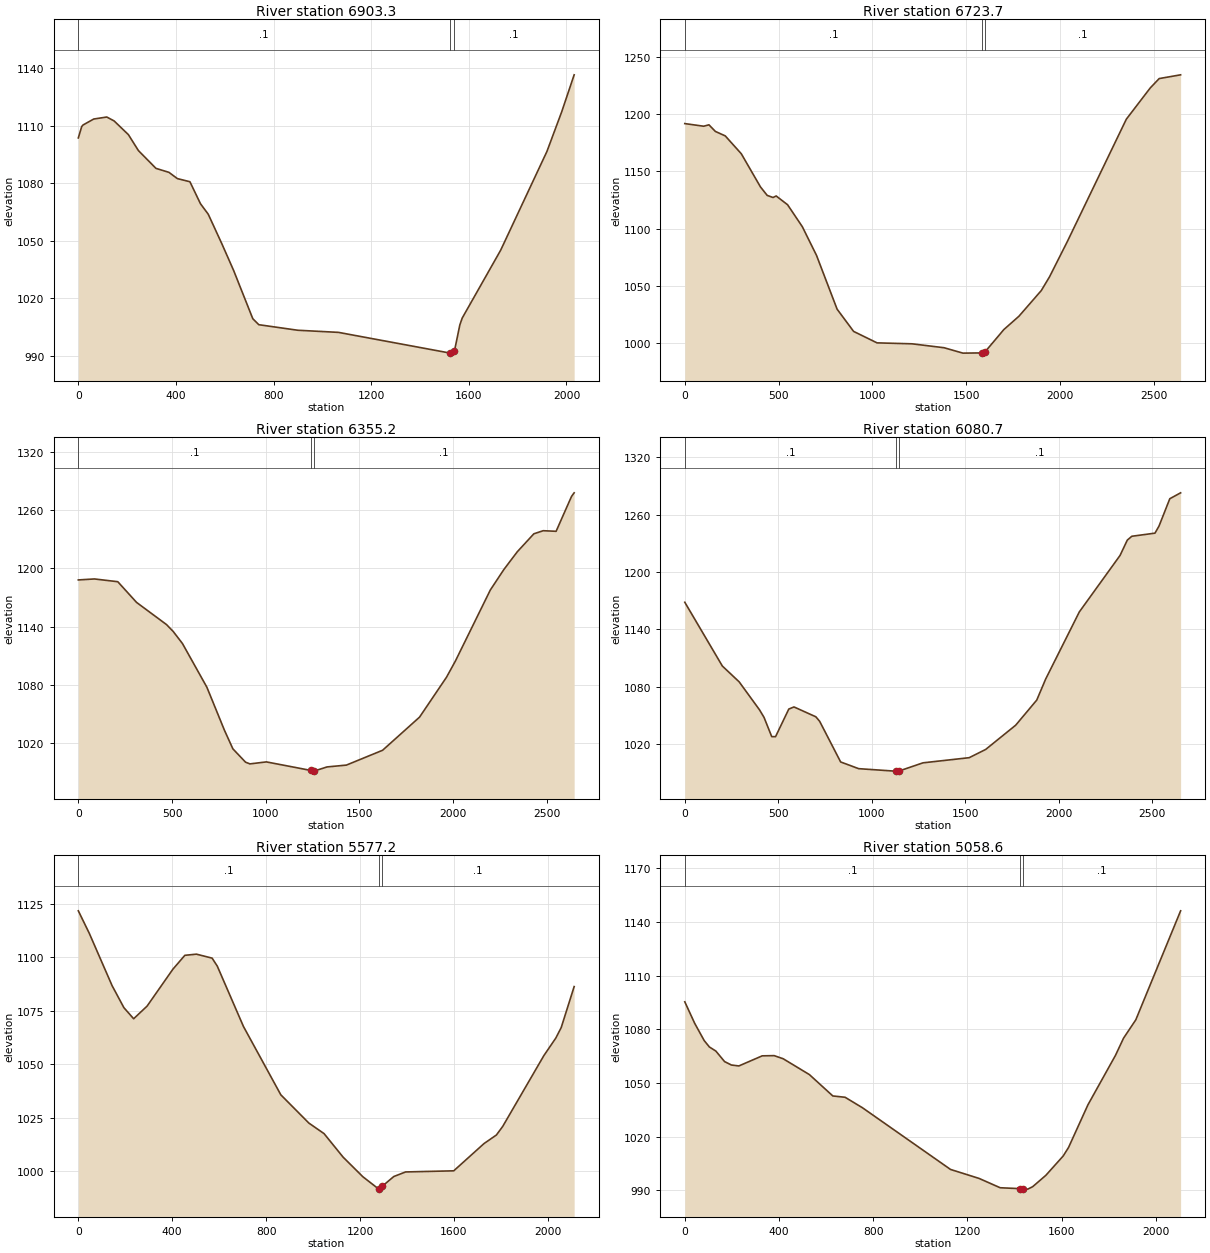
Type RM Length L Ch R = 1 ,6903.3,183.153,179.62,175.92
XS GIS Cut Line= 3
     1691207.735      238186.007     1691347.808      237585.697
     1691717.999      236219.992
#Sta/Elev= 30
       0 1103.67    13.8 1109.55    19.0 1110.37    63.0 1113.50   116.6 1114.55
   146.5 1112.52   205.1 1105.37   246.2 1097.05   318.1 1087.78   371.2 1085.71
   405.7 1082.45   457.2 1080.81   500.3 1069.37   532.4 1063.85   588.2 1048.42
   636.3 1034.55   714.8 1009.40   739.4 1006.28   898.7 1003.39  1065.7 1002.28
  1523.3  991.48  1524.4  991.46  1538.3  992.69  1543.8  994.31  1563.1 1006.19
  1572.8 1009.75  1730.4 1045.14  1919.9 1096.61  1980.3 1117.24  2031.4 1136.55
#Mann= 3 , 0 , 0
       0     0.1       0  1523.3   0.045       0  1538.3     0.1       0
Bank Sta=  1523.3,  1538.3
Exp/Cntr=0.3,0.1

Type RM Length L Ch R = 1 ,6723.7,371.888,368.542,363.895
XS GIS Cut Line= 3
     1691537.121      238414.108     1691671.772      237171.112
     1691804.536      235786.117
#Sta/Elev= 30
       0 1191.75   100.7 1189.45   128.7 1190.67   162.9 1184.92   215.5 1181.02
   300.9 1165.48   403.3 1136.49   439.0 1129.14   470.1 1127.30   486.9 1128.63
   547.7 1120.97   626.2 1101.84   701.9 1076.78   811.4 1029.94   899.4 1010.54
  1024.1 1000.55  1210.3  999.72  1381.3  996.31  1481.7  991.60  1583.2  991.79
  1598.2  992.43  1699.9 1012.15  1780.4 1023.80  1899.3 1046.17  1943.4 1058.21
  2038.4 1089.02  2352.3 1195.57  2479.7 1222.81  2527.4    1231  2641.6 1234.27
#Mann= 3 , 0 , 0
       0     0.1       0  1583.2   0.045       0  1598.2     0.1       0
Bank Sta=  1583.2,  1598.2
Exp/Cntr=0.3,0.1

Type RM Length L Ch R = 1 ,6355.2,277.506,274.491,272.915
XS GIS Cut Line= 3
     1691978.376      238341.324     1691940.125      237089.172
     1691880.378      235696.641
#Sta/Elev= 30
       0 1188.15    86.2 1189.16   210.6 1186.32   310.7 1165.06   470.9 1142.20
   506.3 1135.17   555.7 1122.76   686.3 1077.76   779.7 1033.63   824.9 1014.43
   892.5 1000.70   915.9  998.93  1003.8 1000.99  1240.4  992.24  1255.4  991.60
  1257.7  991.50  1327.4  995.81  1430.8  997.70  1624.0 1012.95  1821.3 1047.04
  1964.9 1088.00  2012.2 1104.58  2199.0 1177.78  2271.4 1198.88  2342.6 1217.04
  2431.3 1235.59  2481.1 1238.78  2550.2 1238.18  2632.3 1273.97  2646.5 1277.75
#Mann= 3 , 0 , 0
       0     0.1       0  1240.4   0.045       0  1255.4     0.1       0
Bank Sta=  1240.4,  1255.4
Exp/Cntr=0.3,0.1

Type RM Length L Ch R = 1 ,6080.7,508.423,503.473,496.515
XS GIS Cut Line= 3
     1692404.077      238252.369     1692188.507      237015.815
     1691931.752      235643.345
#Sta/Elev= 30
       0 1168.19   200.8 1101.48   290.7 1084.92   399.5 1055.66   423.6 1047.78
   464.8 1027.62   485.4 1027.58   556.2 1056.45   584.0 1058.66   700.8 1048.36
   721.4 1043.57   833.4 1001.11   929.8  994.09  1122.6  991.51  1130.2  991.52
  1145.2  991.60  1273.9 1000.19  1520.9 1005.57  1609.1 1014.21  1769.5 1039.57
  1882.2 1065.85  1929.7 1087.80  2109.8 1158.09  2327.6 1217.18  2366.4 1233.23
  2390.6 1237.24  2514.3 1240.50  2536.1 1247.98  2593.7 1276.53  2651.5 1282.69
#Mann= 3 , 0 , 0
       0     0.1       0  1130.2   0.045       0  1145.2     0.1       0
Bank Sta=  1130.2,  1145.2
Exp/Cntr=0.3,0.1

Type RM Length L Ch R = 1 ,5577.2,515.605,518.565,523.43
XS GIS Cut Line= 3
     1693280.430      238082.634     1692637.435      237001.756
     1692191.329      236272.483
#Sta/Elev= 30
       0 1121.63    46.9 1111.06   143.8 1086.66   194.2 1076.35   235.7 1071.17
   292.9 1077.08   403.0 1094.35   453.9 1100.83   503.2 1101.37   570.0 1099.51
   592.0 1095.79   703.7 1067.53   862.8 1035.61   982.4 1022.39  1047.0 1017.47
  1128.1 1006.48  1212.3  997.31  1279.7  991.57  1280.2  991.52  1294.7  992.85
  1344.1  997.41  1394.3  999.55  1599.6 1000.08  1728.7 1012.83  1781.1 1016.81
  1807.9 1020.78  1983.3 1053.90  2034.5 1062.16  2057.4 1067.04  2112.6 1086.21
#Mann= 3 , 0 , 0
       0     0.1       0  1279.7   0.045       0  1294.7     0.1       0
Bank Sta=  1279.7,  1294.7
Exp/Cntr=0.3,0.1

Type RM Length L Ch R = 1 ,5058.6,655.166,660.219,666
XS GIS Cut Line= 4
     1693250.897      237992.911     1693089.136      237237.239
     1692935.727      236657.189     1692680.589      235970.568
#Sta/Elev= 30
       0 1095.34    41.8 1083.37    82.4 1073.66   104.3 1070.10   131.9 1067.79
   168.9 1061.91   197.7 1060.00   229.6 1059.47   328.7 1065.12   379.5 1065.24
   417.7 1063.50   528.9 1054.65   628.5 1042.69   680.7 1041.95   754.4 1036.09
  1128.3 1001.59  1249.5  996.57  1339.2  991.35  1422.2  990.85  1437.2  990.74
  1456.2  990.58  1477.0  991.93  1533.1  998.30  1606.8 1009.13  1629.4 1013.87
  1711.7 1037.72  1828.5 1065.34  1862.9 1074.99  1915.0 1085.27  2105.3 1146.23
#Mann= 3 , 0 , 0
       0     0.1       0  1422.2   0.045       0  1437.2     0.1       0
Bank Sta=  1422.2,  1437.2
Exp/Cntr=0.3,0.1