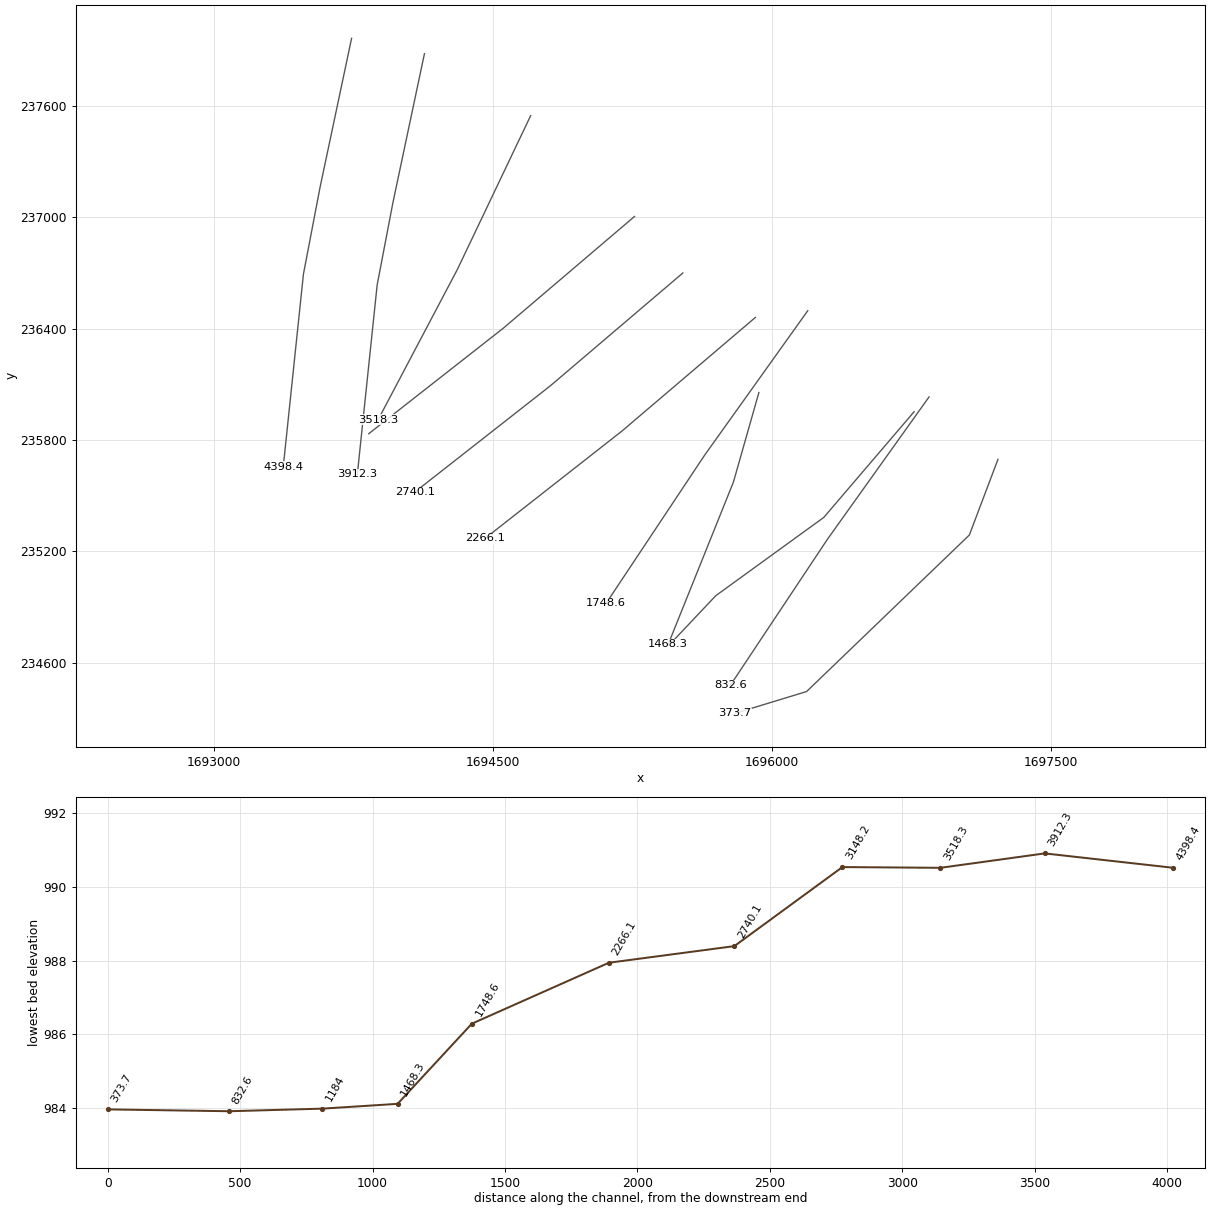
HEC-RAS study KinchloCr.prj: KinchloCr

--- KinchloCr.g01 (geometry) --- (continued)

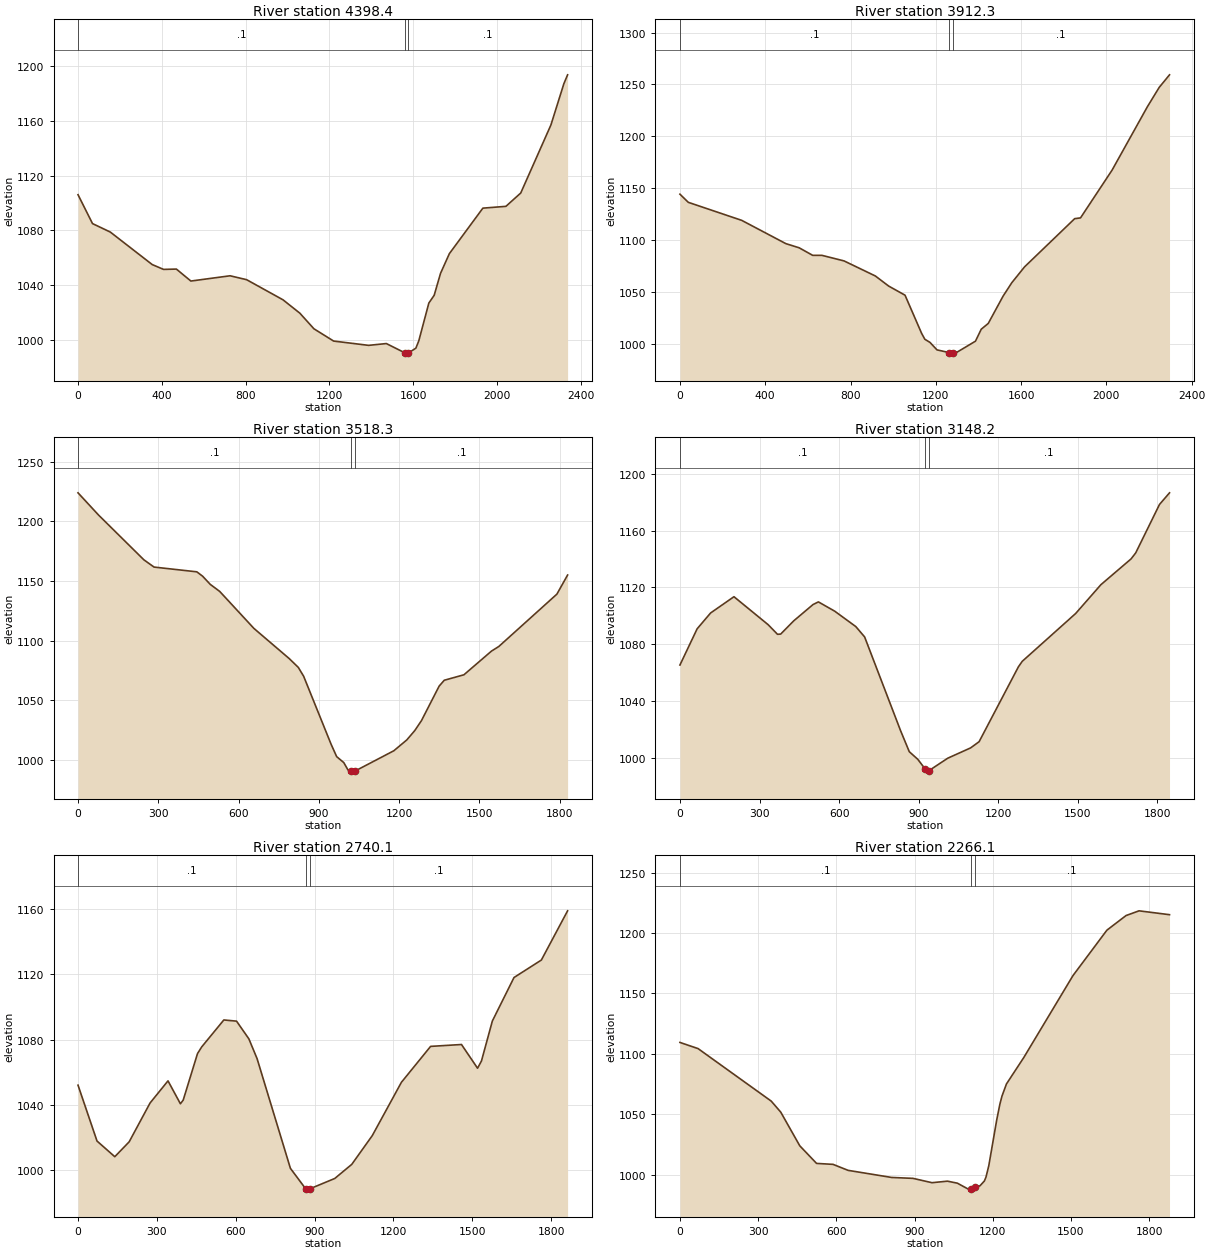
Type RM Length L Ch R = 1 ,4398.4,486.918,486.119,486.514
XS GIS Cut Line= 4
     1693741.163      237962.153     1693571.353      237158.386
     1693482.405      236692.467     1693374.154      235656.425
#Sta/Elev= 30
       0 1106.09    69.2 1085.02   154.2 1078.84   354.3 1055.12   408.5 1051.59
   469.7 1051.83   538.8 1043.10   726.0 1046.94   804.9 1044.10   978.7 1029.41
  1059.1 1019.66  1126.4 1008.26  1220.5  999.31  1387.3  996.18  1472.1  997.49
  1562.5  990.57  1573.1  990.51  1577.5  990.62  1613.1  994.14  1626.9  999.40
  1675.0 1027.04  1700.5 1032.72  1730.9 1048.74  1773.0 1063.08  1933.0 1096.29
  2042.9 1097.60  2113.8 1107.33  2257.8 1156.96  2319.7 1187.08  2337.5 1193.56
#Mann= 3 , 0 , 0
       0     0.1       0  1562.5   0.045       0  1577.5     0.1       0
Bank Sta=  1562.5,  1577.5
Exp/Cntr=0.3,0.1

Type RM Length L Ch R = 1 ,3912.3,400.525,393.996,385.545
XS GIS Cut Line= 4
     1694132.524      237879.471     1693963.523      237079.533
     1693878.481      236634.075     1693771.989      235614.858
#Sta/Elev= 30
       0 1144.19    39.3 1136.33   289.7 1118.95   496.5 1096.52   559.2 1092.47
   622.5 1085.21   665.9 1085.21   769.5 1079.84   916.5 1065.30   978.8 1055.58
  1055.6 1046.78  1133.2 1010.04  1148.4 1004.28  1172.5 1001.26  1205.5  994.02
  1263.6  991.39  1278.6  991.16  1292.0  990.90  1385.9 1002.43  1413.0 1013.97
  1445.9 1019.55  1515.2 1045.80  1555.8 1058.68  1615.8 1074.04  1851.2 1120.59
  1878.5 1121.33  2026.6 1167.42  2192.2 1228.56  2247.6 1247.22  2295.9 1259.31
#Mann= 3 , 0 , 0
       0     0.1       0  1263.6   0.045       0  1278.6     0.1       0
Bank Sta=  1263.6,  1278.6
Exp/Cntr=0.3,0.1

Type RM Length L Ch R = 1 ,3518.3,378.884,370.108,360.619
XS GIS Cut Line= 3
     1694703.051      237545.672     1694308.826      236716.766
     1693884.097      235909.722
#Sta/Elev= 30
       0 1224.00    76.6 1205.40   246.2 1167.79   284.3 1161.70   444.0 1157.72
   465.7 1154.06   494.1 1147.23   529.6 1141.29   657.3 1110.28   789.6 1084.90
   823.3 1077.55   843.3 1070.12   945.4 1013.36   966.7 1002.68   993.3  997.68
  1009.1  991.48  1019.8  990.51  1020.9  990.52  1035.9  990.63  1180.4 1007.59
  1228.9 1016.70  1258.8 1024.56  1283.6 1032.84  1349.8 1061.83  1368.9 1066.75
  1442.4 1071.34  1545.4 1091.21  1572.8 1095.08  1789.9 1139.01  1829.9 1155.03
#Mann= 3 , 0 , 0
       0     0.1       0  1020.9   0.045       0  1035.9     0.1       0
Bank Sta=  1020.9,  1035.9
Exp/Cntr=0.3,0.1

Type RM Length L Ch R = 1 ,3148.2,408.004,408.083,408.875
XS GIS Cut Line= 3
     1695260.888      237003.075     1694556.535      236401.970
     1693833.048      235833.527
#Sta/Elev= 30
       0 1065.28    64.8 1090.78   115.7 1101.96   203.7 1113.40   332.7 1093.68
   367.9 1086.92   379.9 1087.08   429.0 1096.39   501.9 1107.89   522.1 1109.75
   583.9 1103.18   663.1 1092.37   696.4 1085.08   831.6 1019.21   864.8 1004.22
   896.7  998.88   923.4  992.36   931.7  990.53   938.4  990.80  1009.9  999.64
  1095.9 1006.88  1128.1 1011.26  1276.3 1064.02  1290.9 1067.91  1492.1 1101.57
  1587.5 1121.90  1701.3 1140.07  1718.6 1144.27  1808.3 1178.39  1846.1 1186.59
#Mann= 3 , 0 , 0
       0     0.1       0   923.4   0.045       0   938.4     0.1       0
Bank Sta=   923.4,   938.4
Exp/Cntr=0.3,0.1

Type RM Length L Ch R = 1 ,2740.1,471.266,473.974,475.902
XS GIS Cut Line= 3
     1695520.550      236698.813     1694810.033      236092.447
     1694080.174      235518.997
#Sta/Elev= 30
       0 1052.07    72.3 1017.84   139.9 1008.25   194.6 1017.37   274.1 1041.16
   342.3 1054.71   389.5 1040.67   400.1 1042.92   454.5 1071.41   470.7 1075.55
   554.7 1092.02   603.0 1091.29   649.9 1080.45   681.1 1068.34   807.9 1001.13
   866.9  988.39     868  988.41     883  988.66   976.5  994.90  1041.4 1003.57
  1119.4 1021.19  1230.2 1053.84  1341.2 1075.83  1458.7 1076.98  1519.8 1062.45
  1534.6 1066.87  1576.1 1091.37  1658.4 1118.01  1762.5 1128.72  1862.3 1158.87
#Mann= 3 , 0 , 0
       0     0.1       0     868   0.045       0     883     0.1       0
Bank Sta=     868,     883
Exp/Cntr=0.3,0.1

Type RM Length L Ch R = 1 ,2266.1,513.703,517.506,522.09
XS GIS Cut Line= 3
     1695910.279      236459.584     1695193.598      235847.957
     1694457.367      235269.501
#Sta/Elev= 30
       0 1109.36    69.6 1104.25   350.2 1060.80   386.8 1051.66   459.8 1023.80
   524.2 1009.23   587.5 1008.43   645.2 1003.48   812.3  997.60   894.2  996.85
   967.1  993.26  1026.5  994.53  1064.4  992.87  1106.5  987.94  1115.4  988.31
  1130.4  989.31  1151.3  990.70  1168.2  994.71  1174.3  997.90  1185.0 1007.28
  1215.4 1045.14  1227.4 1058.10  1235.8 1065.04  1252.8 1074.98  1319.5 1096.92
  1508.0 1164.66  1638.2 1202.27  1711.6 1214.37  1761.5 1218.29  1878.5 1215.09
#Mann= 3 , 0 , 0
       0     0.1       0  1115.4   0.045       0  1130.4     0.1       0
Bank Sta=  1115.4,  1130.4
Exp/Cntr=0.3,0.1

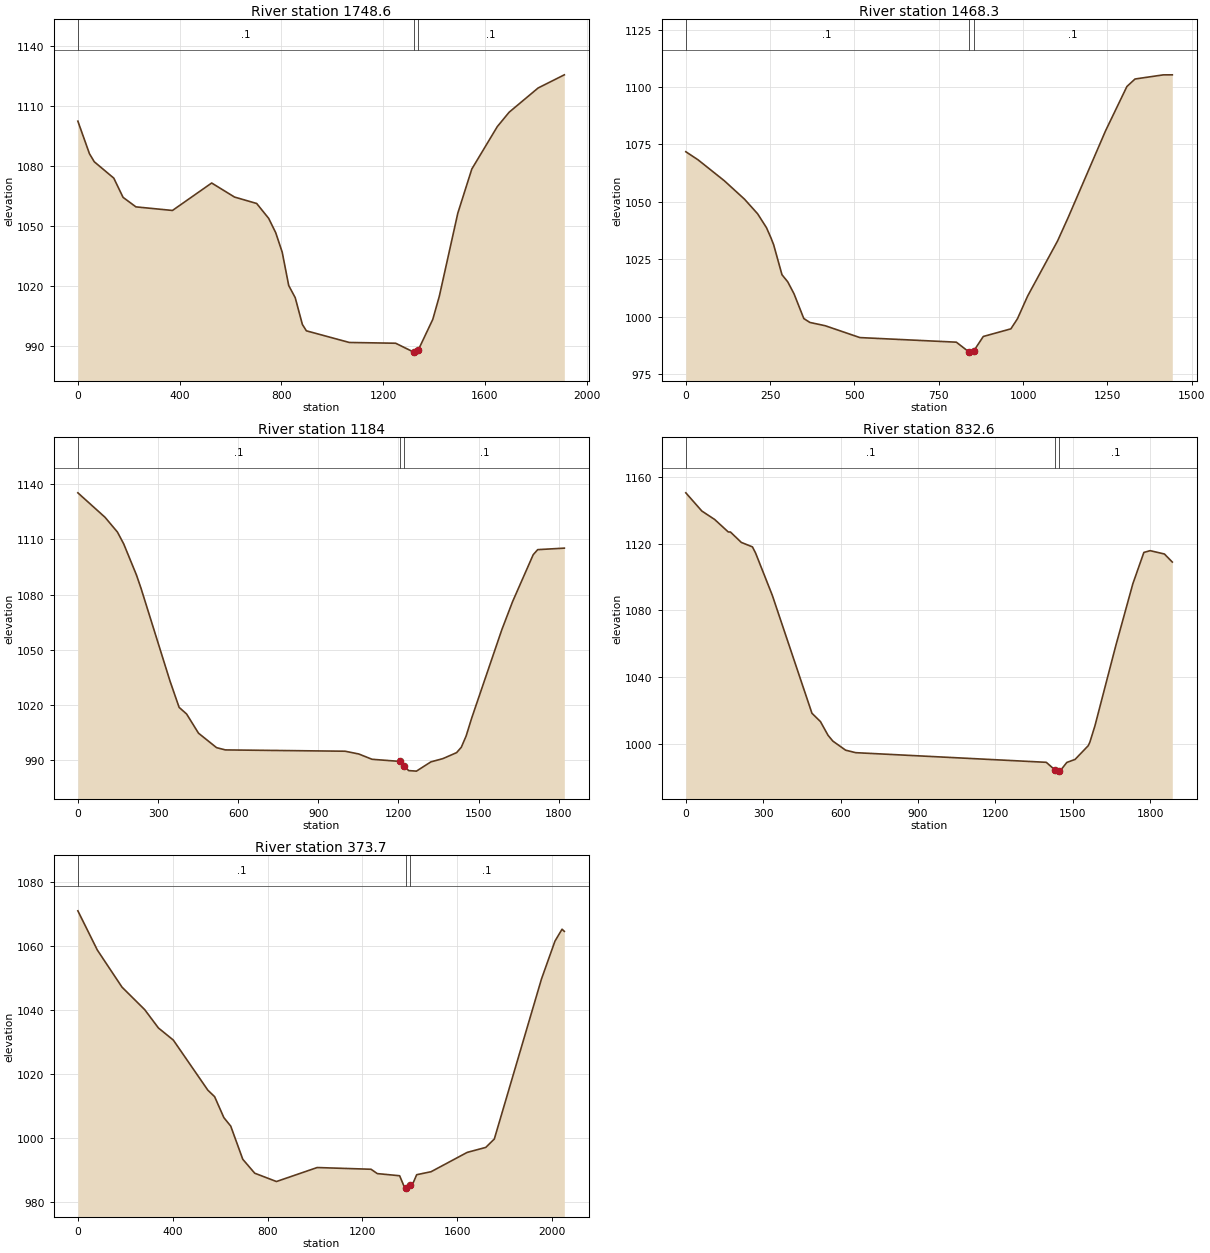
Type RM Length L Ch R = 1 ,1748.6,275.677,280.302,284.927
XS GIS Cut Line= 3
     1696191.562      236495.687     1695636.719      235716.726
     1695108.518      234920.500
#Sta/Elev= 30
       0 1102.55    45.5 1086.25    64.5 1082.20   141.2 1073.99   177.7 1064.35
   228.2 1059.59   371.8 1057.79   525.9 1071.55   615.7 1064.51   702.7 1061.29
   749.9 1053.83   777.6 1046.64   803.1 1036.88   828.7 1020.17   854.2 1014.08
   882.4 1000.66   898.1  997.47  1066.9  991.63  1248.9  991.25  1322.3  986.64
  1324.7  986.29  1337.3  987.70  1394.9 1003.21  1420.6 1014.81  1493.3 1056.46
  1548.3 1078.57  1648.4 1099.81  1694.9 1107.02  1808.8 1119.17  1911.9 1125.77
#Mann= 3 , 0 , 0
       0     0.1       0  1322.3   0.045       0  1337.3     0.1       0
Bank Sta=  1322.3,  1337.3
Exp/Cntr=0.3,0.1

Type RM Length L Ch R = 1 ,1468.3,296.784,284.336,272.017
XS GIS Cut Line= 3
     1695929.131      236055.303     1695792.374      235573.399
     1695441.843      234699.379
#Sta/Elev= 30
       0 1071.83    36.2 1068.32   114.2 1059.19   174.0 1051.17   212.9 1044.81
   239.1 1038.77   252.4 1034.35   260.4 1031.34   285.1 1018.28   302.3 1015.16
   320.7 1010.01   349.9  999.17   368.0  997.48   413.4  996.05   516.2  990.89
   802.2  988.89   838.6  984.75   844.8  984.12   853.6  985.02   882.1  991.37
   963.9  994.69   983.4  999.09  1013.6 1008.98  1102.4 1032.99  1133.9 1043.22
  1244.7 1080.96  1308.0 1100.25  1332.1 1103.51  1415.7 1105.31  1442.6 1105.33
#Mann= 3 , 0 , 0
       0     0.1       0   838.6   0.045       0   853.6     0.1       0
Bank Sta=   838.6,   853.6
Exp/Cntr=0.3,0.1

Type RM Length L Ch R = 1 ,1184,343.666,351.351,358.909
XS GIS Cut Line= 4
     1696762.795      235951.808     1696277.778      235382.929
     1695697.219      234961.273     1695453.337      234702.383
#Sta/Elev= 30
       0 1135.38   101.6 1122.09   148.1 1114.04   171.7 1107.57   219.3 1090.68
   236.5 1083.40   344.9 1032.98   379.0 1018.67   407.0 1015.07   451.5 1004.64
   519.2  996.76   552.2  995.53  1000.1  994.82  1051.3  993.32  1101.1  990.43
  1207.3  989.25  1222.3  986.82  1237.9  984.28  1267.2  983.99  1321.4  989.02
  1366.5  990.81  1417.5  994.04  1435.1  996.96  1453.3 1003.13  1473.6 1012.66
  1586.6 1060.83  1626.8 1076.10  1704.2 1101.70  1721.0 1104.47  1820.8 1105.29
#Mann= 3 , 0 , 0
       0     0.1       0  1207.3   0.045       0  1222.3     0.1       0
Bank Sta=  1207.3,  1222.3
Exp/Cntr=0.3,0.1

Type RM Length L Ch R = 1 ,832.6,462.322,458.973,455.595
XS GIS Cut Line= 3
     1696843.165      236031.560     1696296.027      235263.416
     1695775.168      234478.258
#Sta/Elev= 30
       0 1150.35    62.1 1139.46   111.8 1134.41   164.4 1126.96   172.9 1126.92
   214.9 1120.71   258.2 1118.02   270.4 1114.33   335.1 1089.09   488.8 1018.52
   521.7 1013.56   551.0 1005.38   569.9 1001.86   619.3  996.45   658.1  994.96
  1396.9  989.19  1430.9  984.58  1445.9  984.00  1449.9  983.92  1476.5  989.12
  1508.3  990.90  1559.6  999.14  1565.8 1001.23  1585.4 1010.97  1665.6 1058.55
  1732.4 1095.98  1775.1 1114.70  1799.4 1115.76  1854.7 1113.77  1885.3 1108.95
#Mann= 3 , 0 , 0
       0     0.1       0  1430.9   0.045       0  1445.9     0.1       0
Bank Sta=  1430.9,  1445.9
Exp/Cntr=0.3,0.1

Type RM Length L Ch R = 1 ,373.7,377.582,373.658,369.763
XS GIS Cut Line= 4
     1697213.247      235695.211     1697059.831      235288.325
     1696185.512      234445.648     1695800.506      234328.008
#Sta/Elev= 30
       0 1071.09    82.0 1058.83   186.3 1047.19   282.0 1040.15   339.7 1034.42
   402.6 1030.63   548.3 1014.94   576.8 1012.91   615.8 1006.35   644.8 1003.69
   695.5  993.32   745.8  988.96   837.5  986.35  1009.4  990.73  1236.4  990.19
  1262.9  988.83  1357.1  988.16  1380.6  983.97  1385.2  984.30  1400.2  985.27
  1415.4  986.14  1428.9  988.48  1489.6  989.42  1642.0  995.47  1720.3  997.03
  1756.4  999.66  1955.0 1049.68  2012.1 1061.60  2042.0 1065.33  2051.7 1064.66
#Mann= 3 , 0 , 0
       0     0.1       0  1385.2   0.045       0  1400.2     0.1       0
Bank Sta=  1385.2,  1400.2
Exp/Cntr=0.3,0.1